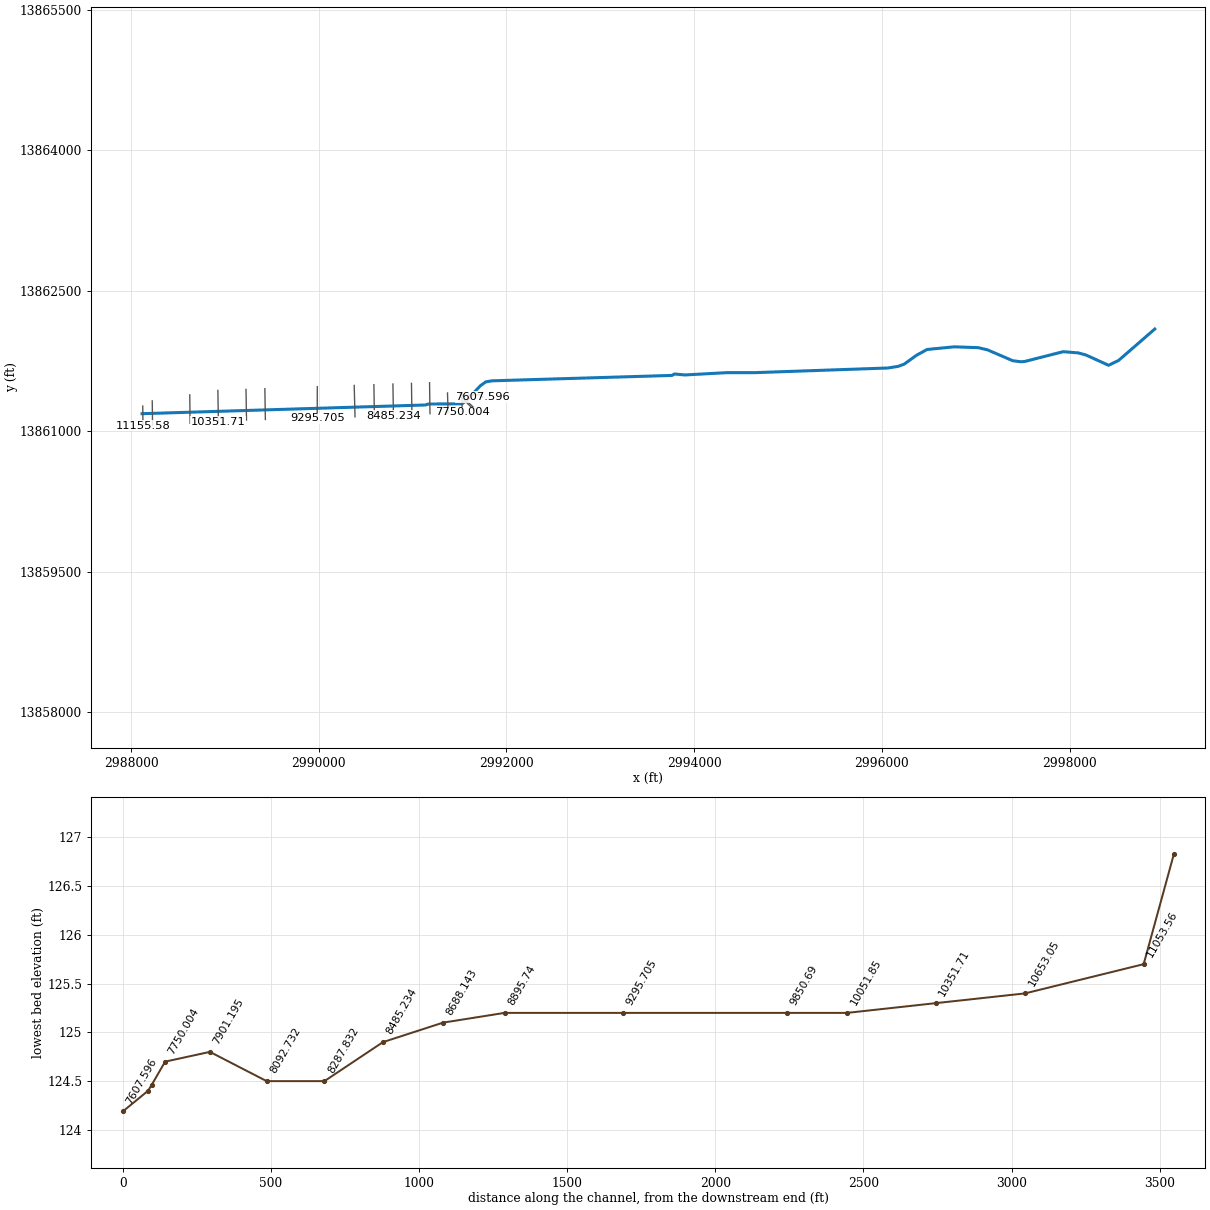
--- U101_08_00.prj (project) ---

Proj Title=U101-08-00 2019 (Re-Study)
Current Plan=p01
Default Exp/Contr=0.3,0.1
English Units
Geom File=g01
Flow File=f01
Flow File=f02
Flow File=f03
Plan File=p01
Plan File=p02
Plan File=p03
Y Axis Title=Elevation
X Axis Title(PF)=Main Channel Distance
X Axis Title(XS)=Station
BEGIN DESCRIPTION:
Tributary 9.6 to South Mayde Creek (U101-08-00)
(Flood Hazard & Floodway) Model
10-, 2-, 1-, and 0.2% Events
Filename U101_08_00.prj
Prepared by:  LAN                               Date: 07/10/2012
Reviewed by: GA                                Date: 07/05/2012
STATUS: Final
ADDICKS WATERSHED MODEL UPDATE
HARRIS COUNTY, TEXAS
END DESCRIPTION:
DSS Export Rating Curves= 0
DSS Export Rating Curve Sorted= 0
DSS Export Volume Flow Curves= 0
DXF OffsetX= 0
DXF OffsetY= 0
DXF ScaleX= 1
DXF ScaleY= 10

--- U101_08_00.p01 (plan) ---

Plan Title=Effective Multi-Profile 2019 (Re-Study)
Program Version=4.10
Short Identifier=Eff+ReStudy MP
Geom File=g01
Flow File=f01
Subcritical Flow
K Sum by GR= 0
Std Step Tol= 0.01
Critical Tol= 0.01
Num of Std Step Trials= 20
Max Error Tol= 0.3
Flow Tol Ratio= 0.001
Split Flow NTrial= 30
Split Flow Tol= 0.02
Split Flow Ratio= 0.02
Log Output Level= 0
Friction Slope Method= 1
Unsteady Friction Slope Method= 2
Unsteady Bridges Friction Slope Method= 1
Parabolic Critical Depth
Global Vel Dist= 0 , 0 , 0
Global Log Level= 0
CheckData=True
Encroach Param=-1 ,0,0, 0
Computation Interval=1HOUR
Output Interval=1HOUR
Run HTab= 0
Run UNet= 0
Run PostProcess= 0
Run WQNet= 0
UNET Theta= 1
UNET Theta Warmup= 1
UNET ZTol= 0.02
UNET ZSATol= 0.05
UNET MxIter= 20
UNET MaxInSteps= 0
UNET DtIC= 0
UNET DtMin= 0
UNET MaxCRTS= 20
UNET WFStab= 2
UNET SFStab= 1
UNET WFX= 1
UNET SFX= 1
UNET DSS MLevel= 4
UNET DZMax Abort= 100
UNET Convert EG Bridges= 0
UNET Use Existing IB Tables=-1
UNET Froude Reduction=False
UNET Froude Limit= 1
UNET Froude Power= 10
UNET Time Slicing=0,0, 5
UNET Junction Losses=0
Instantaneous Interval=1HOUR
Write IC File= 0
Write IC File at Sim End=0
Echo Input=False
Echo Parameters=False
Echo Output=False
Write Detailed= 0
WQ AD Non Conservative
WQ ULTIMATE=-1
WQ Max Comp Step=1HOUR
WQ Output Interval=15MIN
WQ Output Selected Increments= 0
WQ Output face flow=0
WQ Output face velocity=0
WQ Output face area=0
WQ Output face dispersion=0
WQ Output cell volume=0
WQ Output cell surface area=0
WQ Output cell continuity=0
WQ Output cumulative cell continuity=0
WQ Output face conc=0
WQ Output face dconc_dx=0
WQ Output face courant=0
WQ Output face peclet=0
WQ Output face adv mass=0
WQ Output face disp mass=0
WQ Output cell mass=0
WQ Output cell source sink temp=0
WQ Output cell source sink nsm=0
WQ Output MaxMinRange=-1
WQ Daily Max Min Mean=-1
WQ Daily Range=0
WQ Daily Time=0
WQ Create Restart=0
WQ Fixed Restart=0
WQ System Summary=0
WQ Use Fixed Temperature=0
Sorting and Armoring Iterations= 10
XS Update Threshold= 0.02
Hydraulics Update Threshold= 0.02
Energy Slope Method= 1
Volume Change Method= 0
XS Weighting Method= 0
Number of US Weighted Cross Sections= 1
Number of DS Weighted Cross Sections= 1
Upstream XS Weight=0.25
Main XS Weight=0.5
Downstream XS Weight=0.25
Number of DS XS's Weighted with US Boundary= 1
Upstream Boundary Weight= 1
Weight of XSs Associated with US Boundary= 0
Number of US XS's Weighted with DS Boundary= 1
Downstream Boundary Weight= 0.5
Weight of XSs Associated with DS Boundary= 0.5
Sediment Output Level= 4
Mass or Volume Output= 0
Output Increment Type= 1
Profile and TS Output Increment= 10
XS Output Flag= 0
XS Output Increment= 10
Disregard all LS=0
Disregard all Conn=0
Disregard all Breaches=0
Disregard all Pumps=0

--- U101_08_00.p02 (plan) ---

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Plan Title=Effective Floodway 2019 (Re-Study)
Short Identifier=Eff+ReStudy FW
Geom File=g01
Flow File=f02
Encroach Param=-1 ,0,0, 2
Encroach River=U101-08-00
Encroach Reach=U101-08-00_0002
Encroach Node=11155.58
       1   29.31  146.57
Encroach Node=11053.56
       1   79.13  196.39
Encroach Node=10653.05
       1  127.27   248.7
Encroach Node=10351.71
       1  162.84  291.31
Encroach Node=10051.85
       1  165.19  288.37
Encroach Node=9850.69
       1  166.73   294.8
Encroach Node=9295.705
       1  170.77  290.19
Encroach Node=8895.74
       1  173.95  291.61
Encroach Node=8688.143
       1  172.57  290.72
Encroach Node=8485.234
       1  174.99  293.19
Encroach Node=8287.832
       1   177.5  290.73
Encroach Node=8092.732
       1  177.73  296.21
Encroach Node=7901.195
       1    57.5   182.5
Encroach Node=7750.004
       1      50     175
Encroach Node=7704.322
       1    52.6  165.91
Encroach Node=7691.996
       1    52.3  164.14
Encroach Node=7607.596
       1  37.655 157.339
Encroach Node=7589.07
       1  40.479  160.17
Encroach Node=7525.309
       1  40.479 167.208
Encroach Node=7456.862
       1  107.35  230.25
Encroach Node=7295.447
       1   137.4   264.8
Encroach Node=6523.721
       1    85.5  207.05
Encroach Node=5714.47
       1   67.04  189.54
Encroach Node=5309.224
       1   62.84  179.96
Encroach Node=5073.266
       1   59.21  183.85
Encroach Node=5058.191
       1    64.2  183.85
Encroach Node=4890.756
       1   59.52  182.59
Encroach Node=4872.718
       1   59.52  177.67
Encroach Node=4122.137
       1  200.86  324.19
Encroach Node=3440.281
       1 1414.56 1539.56
Encroach Node=3430.281
       1 1417.59 1542.59
Encroach Node=3335.073
       1 1428.38 1551.33
Encroach Node=3325.073
       1 1430.96 1553.91
Encroach Node=3176.741
       1 1468.47 1588.08
Encroach Node=3159.739
       1 1462.76 1592.13
Encroach Node=3101.097
       1 1467.73 1592.13
Encroach Node=3046.937
       1 1446.72 1570.81
Encroach Node=2535.291
       1 1104.54 1224.02
Encroach Node=2455.761
       1   157.1  276.66
Encroach Node=2335.474
       1  154.61  274.17
Encroach Node=2330.317
       1  154.64  274.24
Encroach Node=2017.84
       1   19.12  146.02
Encroach Node=1526.611
       1   54.87  144.65
Encroach Node=1478.421
       1   59.29  153.18
Encroach Node=1287.94
       1   64.24  148.23
Encroach Node=1278.983
       1   64.55   158.9
Encroach Node=1098.127
       1    45.5   141.7
Encroach Node=890.525
       1   44.35  131.66
Encroach Node=688.6711
       1   44.01  127.23
Encroach Node=533.9202
       1   31.46  111.46
Encroach Node=521.9677
       1   35.13  106.97
Encroach Node=161.0575
       1   50.81  129.29

--- U101_08_00.p03 (plan) ---

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Plan Title=Storage Routing (SV-SQ)
Short Identifier=SV-SQ
Geom File=g01
Flow File=f03

--- U101_08_00.f01 (steady flow) ---

Flow Title=Effective Multi-Profile 2019 (Re-Study)
Program Version=4.10
Number of Profiles= 4
Profile Names=10YR,50YR,100YR,500YR
River Rch & RM=U101-08-00,U101-08-00_0002 ,11155.58
     108     118     207     430
River Rch & RM=U101-08-00,U101-08-00_0002 ,11053.56
     114     128     218     444
River Rch & RM=U101-08-00,U101-08-00_0002 ,10653.05
     119     136     227     455
River Rch & RM=U101-08-00,U101-08-00_0002 ,10351.71
     125     145     237     467
River Rch & RM=U101-08-00,U101-08-00_0002 ,10051.85
     128     151     243     474
River Rch & RM=U101-08-00,U101-08-00_0002 ,9850.69
     139     168     262     496
River Rch & RM=U101-08-00,U101-08-00_0002 ,9295.705
     147     182     277     512
River Rch & RM=U101-08-00,U101-08-00_0002 ,8895.74
     152     190     285     521
River Rch & RM=U101-08-00,U101-08-00_0002 ,8688.143
     156     198     293     530
River Rch & RM=U101-08-00,U101-08-00_0002 ,8485.234
     161     206     301     538
River Rch & RM=U101-08-00,U101-08-00_0002 ,8287.832
     165     214     309     547
River Rch & RM=U101-08-00,U101-08-00_0002 ,8092.732
     170     223     317     556
River Rch & RM=U101-08-00,U101-08-00_0002 ,7901.195
     175     232     325     564
River Rch & RM=U101-08-00,U101-08-00_0002 ,7704.322
     181     243     336     576
River Rch & RM=U101-08-00,U101-08-00_0002 ,7456.862
     185     251     344     583
River Rch & RM=U101-08-00,U101-08-00_0002 ,7295.447
     207     293     381     621
River Rch & RM=U101-08-00,U101-08-00_0002 ,6523.721
     232     345     426     663
River Rch & RM=U101-08-00,U101-08-00_0002 ,5714.47
     246     374     450     685
River Rch & RM=U101-08-00,U101-08-00_0002 ,5309.224
     254     392     464     699
River Rch & RM=U101-08-00,U101-08-00_0002 ,5073.266
     255     393     465     700
River Rch & RM=U101-08-00,U101-08-00_0002 ,5058.191
     344     578     684     987
River Rch & RM=U101-08-00,U101-08-00_0002 ,4890.756
     345     579     685     989
River Rch & RM=U101-08-00,U101-08-00_0002 ,4872.718
     369     614     734    1066
River Rch & RM=U101-08-00,U101-08-00_0002 ,4122.137
     392     647     782    1140
River Rch & RM=U101-08-00,U101-08-00_0002 ,3440.281
     393     648     783    1141
River Rch & RM=U101-08-00,U101-08-00_0002 ,3430.281
     384     571     703    1083
River Rch & RM=U101-08-00,U101-08-00_0002 ,3335.073
     391     584     716    1105
River Rch & RM=U101-08-00,U101-08-00_0002 ,3046.937
     407     610     745    1152
River Rch & RM=U101-08-00,U101-08-00_0002 ,2455.761
     419     630     768    1188
River Rch & RM=U101-08-00,U101-08-00_0002 ,2017.84
     435     656     796    1234
River Rch & RM=U101-08-00,U101-08-00_0002 ,1478.421
     453     685     828    1285
River Rch & RM=U101-08-00,U101-08-00_0002 ,890.525
     464     705     849    1319
River Rch & RM=U101-08-00,U101-08-00_0002 ,521.9677
     476     724     870    1353
Boundary for River Rch & Prof#=U101-08-00,U101-08-00_0002 , 1
Up Type= 0
Dn Type= 3
Dn Slope=0.00066
Boundary for River Rch & Prof#=U101-08-00,U101-08-00_0002 , 2
Up Type= 0
Dn Type= 3
Dn Slope=0.00066
Boundary for River Rch & Prof#=U101-08-00,U101-08-00_0002 , 3
Up Type= 0
Dn Type= 3
Dn Slope=0.00066
Boundary for River Rch & Prof#=U101-08-00,U101-08-00_0002 , 4
Up Type= 0
Dn Type= 3
Dn Slope=0.00066
Observed WS=U101-08-00      ,U101-08-00_0002 ,11155.58,0,132.36,134.42,136.12,138.06
Observed WS=U101-08-00      ,U101-08-00_0002 ,11053.56,0,132.36,134.42,136.12,138.06
Observed WS=U101-08-00      ,U101-08-00_0002 ,10653.05,0,132.32,134.4,136.11,138.05
Observed WS=U101-08-00      ,U101-08-00_0002 ,10351.71,0,132.29,134.38,136.1,138.05
Observed WS=U101-08-00      ,U101-08-00_0002 ,10051.85,0,132.26,134.37,136.09,138.04
Observed WS=U101-08-00      ,U101-08-00_0002 ,9850.69 ,0,132.25,134.36,136.09,138.04
Observed WS=U101-08-00      ,U101-08-00_0002 ,9295.705,0,132.22,134.34,136.08,138.03
Observed WS=U101-08-00      ,U101-08-00_0002 ,8895.74 ,0,132.2,134.33,136.07,138.03
Observed WS=U101-08-00      ,U101-08-00_0002 ,8688.143,0,132.19,134.33,136.07,138.02
Observed WS=U101-08-00      ,U101-08-00_0002 ,8485.234,0,132.18,134.32,136.07,138.02
Observed WS=U101-08-00      ,U101-08-00_0002 ,8287.832,0,132.18,134.32,136.07,138.02
Observed WS=U101-08-00      ,U101-08-00_0002 ,8092.732,0,132.17,134.31,136.06,138.01
Observed WS=U101-08-00      ,U101-08-00_0002 ,7901.195,0,132.16,134.31,136.06,138.01
Observed WS=U101-08-00      ,U101-08-00_0002 ,7750.004,0,131.91,133.81,135.42,137.36
Observed WS=U101-08-00      ,U101-08-00_0002 ,7691.996,0,131.9,133.81,135.42,137.35
Observed WS=U101-08-00      ,U101-08-00_0002 ,7607.596,0,131.9,133.81,135.41,137.35
Observed WS=U101-08-00      ,U101-08-00_0002 ,7589.07 ,0,131.9,133.8,135.41,137.35
Observed WS=U101-08-00      ,U101-08-00_0002 ,7525.309,0,131.34,132.84,134.1,136.06
Observed WS=U101-08-00      ,U101-08-00_0002 ,7456.862,0,131.32,132.83,134.09,136.05
Observed WS=U101-08-00      ,U101-08-00_0002 ,7295.447,0,131.29,132.8,134.07,136.04
Observed WS=U101-08-00      ,U101-08-00_0002 ,6523.721,0,131.11,132.67,133.99,135.99
Observed WS=U101-08-00      ,U101-08-00_0002 ,5714.47 ,0,130.94,132.55,133.92,135.95
Observed WS=U101-08-00      ,U101-08-00_0002 ,5309.224,0,130.88,132.5,133.89,135.93
Observed WS=U101-08-00      ,U101-08-00_0002 ,4890.756,0,130.77,132.41,133.83,135.88
Observed WS=U101-08-00      ,U101-08-00_0002 ,4872.718,0,130.76,132.4,133.82,135.88
Observed WS=U101-08-00      ,U101-08-00_0002 ,4122.137,0,130.51,132.21,133.7,135.79
Observed WS=U101-08-00      ,U101-08-00_0002 ,3440.281,0,130.37,132.12,133.65,135.75
Observed WS=U101-08-00      ,U101-08-00_0002 ,3176.741,0,130.33,132.09,133.63,135.74
Observed WS=U101-08-00      ,U101-08-00_0002 ,3159.739,0,130.33,132.09,133.63,135.74
Observed WS=U101-08-00      ,U101-08-00_0002 ,3101.097,0,129.32,130.62,131.68,135.11
Observed WS=U101-08-00      ,U101-08-00_0002 ,3046.937,0,129.28,130.6,131.66,135.11
Observed WS=U101-08-00      ,U101-08-00_0002 ,2535.291,0,129.13,130.5,131.59,135.08
Observed WS=U101-08-00      ,U101-08-00_0002 ,2455.761,0,129.11,130.48,131.58,135.07
Observed WS=U101-08-00      ,U101-08-00_0002 ,2335.474,0,127.41,128.51,129.44,132.38
Observed WS=U101-08-00      ,U101-08-00_0002 ,2330.317,0,127.37,128.48,129.42,132.37
Observed WS=U101-08-00      ,U101-08-00_0002 ,2017.84 ,0,126.93,128.24,129.26,132.31
Observed WS=U101-08-00      ,U101-08-00_0002 ,1526.611,0,126.45,127.95,129.07,132.22
Observed WS=U101-08-00      ,U101-08-00_0002 ,1478.421,0,126.42,127.93,129.05,132.22
Observed WS=U101-08-00      ,U101-08-00_0002 ,1287.94 ,0,125.05,125.61,125.96,126.88
Observed WS=U101-08-00      ,U101-08-00_0002 ,1278.983,0,125.02,125.59,125.93,126.85
Observed WS=U101-08-00      ,U101-08-00_0002 ,1098.127,0,124.57,125.12,125.45,126.34
Observed WS=U101-08-00      ,U101-08-00_0002 ,890.525 ,0,124.07,124.61,124.93,125.77
Observed WS=U101-08-00      ,U101-08-00_0002 ,688.6711,0,123.52,124.02,124.33,125.1
Observed WS=U101-08-00      ,U101-08-00_0002 ,533.9202,0,121.51,121.91,122.15,123.11
Observed WS=U101-08-00      ,U101-08-00_0002 ,521.9677,0,120.93,121.74,122.24,123.59
Observed WS=U101-08-00      ,U101-08-00_0002 ,161.0575,0,120.72,121.55,122.05,123.42
DSS Import GetInterval= 0
DSS Import GetPeak= 0
DSS Import FillOption= 0

--- U101_08_00.f02 (steady flow) ---

Flow Title=Effective Floodway 2019 (Re-Study)
Program Version=4.10
Number of Profiles= 2
Profile Names=100YR,FW
River Rch & RM=U101-08-00,U101-08-00_0002 ,11155.58
     207     207
River Rch & RM=U101-08-00,U101-08-00_0002 ,11053.56
     218     218
River Rch & RM=U101-08-00,U101-08-00_0002 ,10653.05
     227     227
River Rch & RM=U101-08-00,U101-08-00_0002 ,10351.71
     237     237
River Rch & RM=U101-08-00,U101-08-00_0002 ,10051.85
     243     243
River Rch & RM=U101-08-00,U101-08-00_0002 ,9850.69
     262     262
River Rch & RM=U101-08-00,U101-08-00_0002 ,9295.705
     277     277
River Rch & RM=U101-08-00,U101-08-00_0002 ,8895.74
     285     285
River Rch & RM=U101-08-00,U101-08-00_0002 ,8688.143
     293     293
River Rch & RM=U101-08-00,U101-08-00_0002 ,8485.234
     301     301
River Rch & RM=U101-08-00,U101-08-00_0002 ,8287.832
     309     309
River Rch & RM=U101-08-00,U101-08-00_0002 ,8092.732
     317     317
River Rch & RM=U101-08-00,U101-08-00_0002 ,7901.195
     325     325
River Rch & RM=U101-08-00,U101-08-00_0002 ,7704.322
     336     336
River Rch & RM=U101-08-00,U101-08-00_0002 ,7456.862
     344     344
River Rch & RM=U101-08-00,U101-08-00_0002 ,7295.447
     381     381
River Rch & RM=U101-08-00,U101-08-00_0002 ,6523.721
     426     426
River Rch & RM=U101-08-00,U101-08-00_0002 ,5714.47
     450     450
River Rch & RM=U101-08-00,U101-08-00_0002 ,5309.224
     464     464
River Rch & RM=U101-08-00,U101-08-00_0002 ,5073.266
     465     465
River Rch & RM=U101-08-00,U101-08-00_0002 ,5058.191
     684     684
River Rch & RM=U101-08-00,U101-08-00_0002 ,4890.756
     685     685
River Rch & RM=U101-08-00,U101-08-00_0002 ,4872.718
     734     734
River Rch & RM=U101-08-00,U101-08-00_0002 ,4122.137
     782     782
River Rch & RM=U101-08-00,U101-08-00_0002 ,3440.281
     783     783
River Rch & RM=U101-08-00,U101-08-00_0002 ,3430.281
     703     703
River Rch & RM=U101-08-00,U101-08-00_0002 ,3335.073
     716     716
River Rch & RM=U101-08-00,U101-08-00_0002 ,3046.937
     745     745
River Rch & RM=U101-08-00,U101-08-00_0002 ,2455.761
     768     768
River Rch & RM=U101-08-00,U101-08-00_0002 ,2017.84
     796     796
River Rch & RM=U101-08-00,U101-08-00_0002 ,1478.421
     828     828
River Rch & RM=U101-08-00,U101-08-00_0002 ,890.525
     849     849
River Rch & RM=U101-08-00,U101-08-00_0002 ,521.9677
     870     870
Boundary for River Rch & Prof#=U101-08-00,U101-08-00_0002 , 1
Up Type= 0
Dn Type= 3
Dn Slope=0.00066
Boundary for River Rch & Prof#=U101-08-00,U101-08-00_0002 , 2
Up Type= 0
Dn Type= 3
Dn Slope=0.00066
Observed WS=U101-08-00      ,U101-08-00_0002 ,11155.58,0,132.36,134.42
Observed WS=U101-08-00      ,U101-08-00_0002 ,11053.56,0,132.36,134.42
Observed WS=U101-08-00      ,U101-08-00_0002 ,10653.05,0,132.32,134.4
Observed WS=U101-08-00      ,U101-08-00_0002 ,10351.71,0,132.29,134.38
Observed WS=U101-08-00      ,U101-08-00_0002 ,10051.85,0,132.26,134.37
Observed WS=U101-08-00      ,U101-08-00_0002 ,9850.69 ,0,132.25,134.36
Observed WS=U101-08-00      ,U101-08-00_0002 ,9295.705,0,132.22,134.34
Observed WS=U101-08-00      ,U101-08-00_0002 ,8895.74 ,0,132.2,134.33
Observed WS=U101-08-00      ,U101-08-00_0002 ,8688.143,0,132.19,134.33
Observed WS=U101-08-00      ,U101-08-00_0002 ,8485.234,0,132.18,134.32
Observed WS=U101-08-00      ,U101-08-00_0002 ,8287.832,0,132.18,134.32
Observed WS=U101-08-00      ,U101-08-00_0002 ,8092.732,0,132.17,134.31
Observed WS=U101-08-00      ,U101-08-00_0002 ,7901.195,0,132.16,134.31
Observed WS=U101-08-00      ,U101-08-00_0002 ,7750.004,0,131.91,133.81
Observed WS=U101-08-00      ,U101-08-00_0002 ,7691.996,0,131.9,133.81
Observed WS=U101-08-00      ,U101-08-00_0002 ,7607.596,0,131.9,133.81
Observed WS=U101-08-00      ,U101-08-00_0002 ,7589.07 ,0,131.9,133.8
Observed WS=U101-08-00      ,U101-08-00_0002 ,7525.309,0,131.34,132.84
Observed WS=U101-08-00      ,U101-08-00_0002 ,7456.862,0,131.32,132.83
Observed WS=U101-08-00      ,U101-08-00_0002 ,7295.447,0,131.29,132.8
Observed WS=U101-08-00      ,U101-08-00_0002 ,6523.721,0,131.11,132.67
Observed WS=U101-08-00      ,U101-08-00_0002 ,5714.47 ,0,130.94,132.55
Observed WS=U101-08-00      ,U101-08-00_0002 ,5309.224,0,130.88,132.5
Observed WS=U101-08-00      ,U101-08-00_0002 ,4890.756,0,130.77,132.41
Observed WS=U101-08-00      ,U101-08-00_0002 ,4872.718,0,130.76,132.4
Observed WS=U101-08-00      ,U101-08-00_0002 ,4122.137,0,130.51,132.21
Observed WS=U101-08-00      ,U101-08-00_0002 ,3440.281,0,130.37,132.12
Observed WS=U101-08-00      ,U101-08-00_0002 ,3176.741,0,130.33,132.09
Observed WS=U101-08-00      ,U101-08-00_0002 ,3159.739,0,130.33,132.09
Observed WS=U101-08-00      ,U101-08-00_0002 ,3101.097,0,129.32,130.62
Observed WS=U101-08-00      ,U101-08-00_0002 ,3046.937,0,129.28,130.6
Observed WS=U101-08-00      ,U101-08-00_0002 ,2535.291,0,129.13,130.5
Observed WS=U101-08-00      ,U101-08-00_0002 ,2455.761,0,129.11,130.48
Observed WS=U101-08-00      ,U101-08-00_0002 ,2335.474,0,127.41,128.51
Observed WS=U101-08-00      ,U101-08-00_0002 ,2330.317,0,127.37,128.48
Observed WS=U101-08-00      ,U101-08-00_0002 ,2017.84 ,0,126.93,128.24
Observed WS=U101-08-00      ,U101-08-00_0002 ,1526.611,0,126.45,127.95
Observed WS=U101-08-00      ,U101-08-00_0002 ,1478.421,0,126.42,127.93
Observed WS=U101-08-00      ,U101-08-00_0002 ,1287.94 ,0,125.05,125.61
Observed WS=U101-08-00      ,U101-08-00_0002 ,1278.983,0,125.02,125.59
Observed WS=U101-08-00      ,U101-08-00_0002 ,1098.127,0,124.57,125.12
Observed WS=U101-08-00      ,U101-08-00_0002 ,890.525 ,0,124.07,124.61
Observed WS=U101-08-00      ,U101-08-00_0002 ,688.6711,0,123.52,124.02
Observed WS=U101-08-00      ,U101-08-00_0002 ,533.9202,0,121.51,121.91
Observed WS=U101-08-00      ,U101-08-00_0002 ,521.9677,0,120.93,121.74
Observed WS=U101-08-00      ,U101-08-00_0002 ,161.0575,0,120.72,121.55
DSS Import GetInterval= 0
DSS Import GetPeak= 0
DSS Import FillOption= 0

--- U101_08_00.f03 (steady flow) ---

Flow Title=Storage Routing Flows
Program Version=4.10
Number of Profiles= 8
Profile Names=0.2,0.4,0.6,0.8,1,1.2,1.5,2
River Rch & RM=U101-08-00,U101-08-00_0002 ,11155.58
      93     186     279     372     465     558     698     930
River Rch & RM=U101-08-00,U101-08-00_0002 ,5058.191
     156     313     469     626     782     938    1173    1564
River Rch & RM=U101-08-00,U101-08-00_0002 ,3430.281
     174     348     523     697     871    1045    1307    1742
Boundary for River Rch & Prof#=U101-08-00,U101-08-00_0002 , 1
Up Type= 0
Dn Type= 3
Dn Slope=0.00066
Boundary for River Rch & Prof#=U101-08-00,U101-08-00_0002 , 2
Up Type= 0
Dn Type= 3
Dn Slope=0.00066
Boundary for River Rch & Prof#=U101-08-00,U101-08-00_0002 , 3
Up Type= 0
Dn Type= 3
Dn Slope=0.00066
Boundary for River Rch & Prof#=U101-08-00,U101-08-00_0002 , 4
Up Type= 0
Dn Type= 3
Dn Slope=0.00066
Boundary for River Rch & Prof#=U101-08-00,U101-08-00_0002 , 5
Up Type= 0
Dn Type= 3
Dn Slope=0.00066
Boundary for River Rch & Prof#=U101-08-00,U101-08-00_0002 , 6
Up Type= 0
Dn Type= 3
Dn Slope=0.00066
Boundary for River Rch & Prof#=U101-08-00,U101-08-00_0002 , 7
Up Type= 0
Dn Type= 3
Dn Slope=0.00066
Boundary for River Rch & Prof#=U101-08-00,U101-08-00_0002 , 8
Up Type= 0
Dn Type= 3
Dn Slope=0.00066
DSS Import GetInterval= 0
DSS Import GetPeak= 0
DSS Import FillOption= 0

--- U101_08_00.g01 (geometry) ---

Geom Title=U101-08-00 2019 (Re-Study)
Program Version=4.10

River Reach=U101-08-00      ,U101-08-00_0002
Reach XY= 30
 2988116.753606213861185.75811322991141.1284629413861278.7864704
 2991162.605782213861288.69918032991526.0686379413861291.1771937
2991581.4143277713861334.13183222991721.0170669413861483.6472812
 2991778.840770213861524.95002012991843.2727279413861536.5146295
2993763.8440180313861594.3383328 2993790.277692213861609.2073975
2993900.9687437713861599.29468772994352.5741397713861624.0505437
2994648.6749255213861623.93440222996062.4634365313861673.4972952
2996173.3608525213861690.84437332996238.4125596913861715.0063985
2996366.65705386 13861807.937315 2996481.271982113861871.1304301
2996772.4551267813861899.62906082997026.1022572813861890.6691049
2997124.40225753 13861867.5395582997392.8692402813861751.8924796
 2997477.126617713861740.3275421 2997520.081256213861742.8058836
2997932.2815472813861847.71446642998092.5354918513861834.4976294
2998174.3148558613861812.1941963 2998415.522050613861702.3292585
2998522.08253303 13861754.3704932998907.7969846913862089.5289434

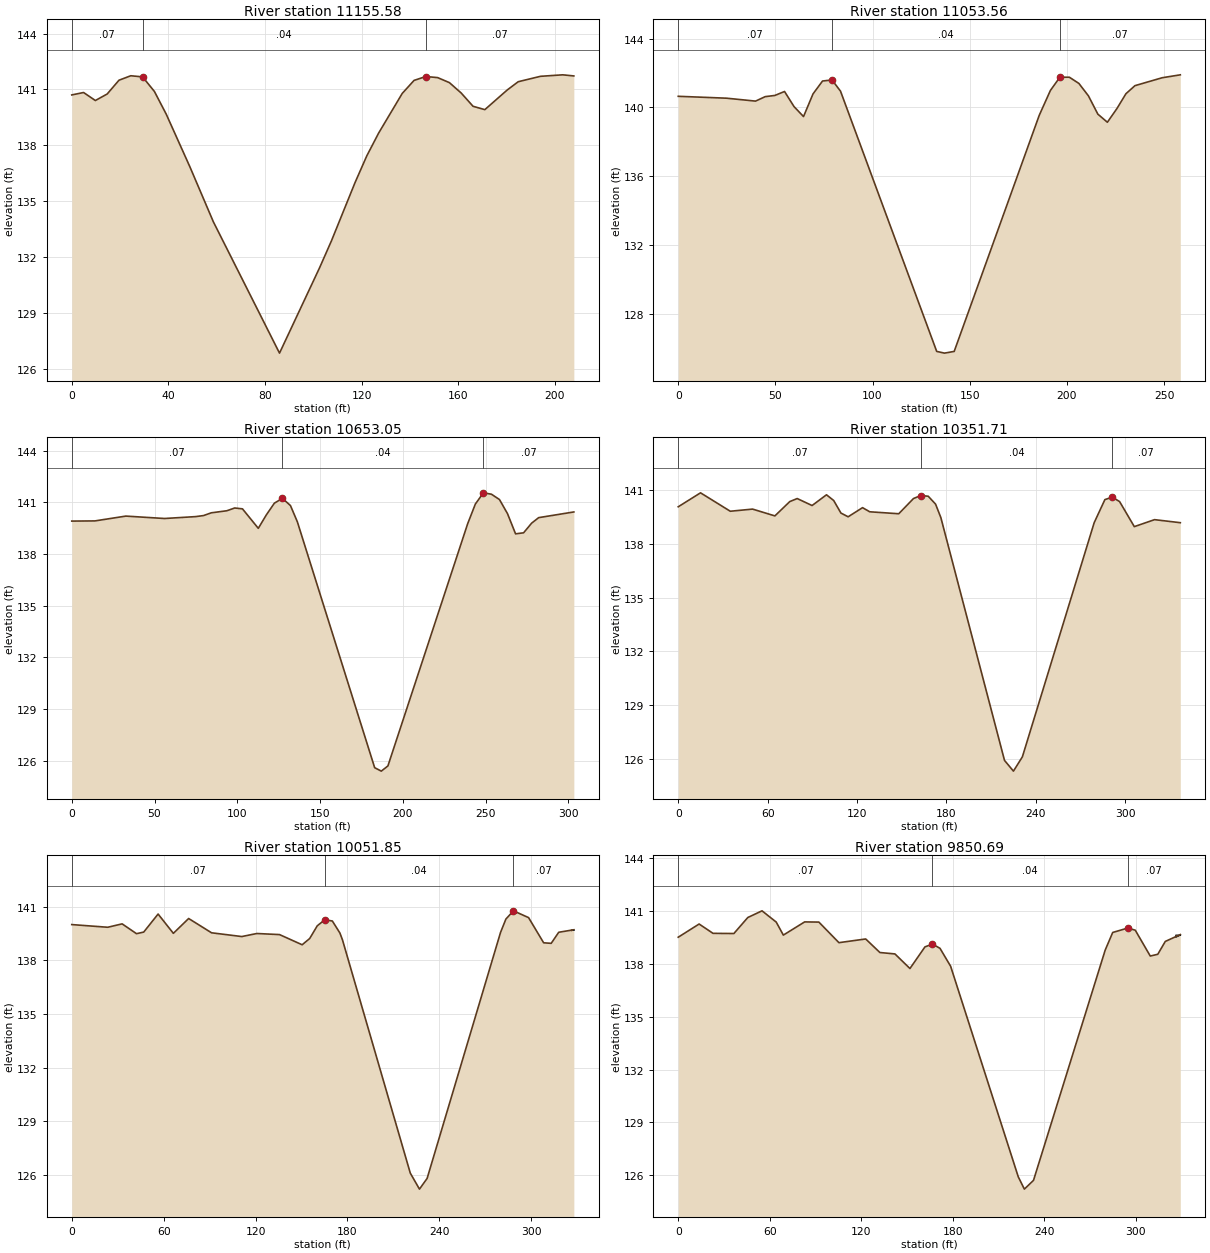
Type RM Length L Ch R = 1 ,11155.58,102,102.01,102.01
Node Name=M
XS GIS Cut Line= 3
2988124.1259667713861267.05913172988126.1840335313861096.0716128
2988126.6276021913861059.2324476
#Sta/Elev= 30
       0   140.7    4.89  140.83    9.77   140.4   14.66  140.75   19.54  141.49
   24.43  141.73   29.31  141.67    34.2  140.89   39.09  139.67   48.86  136.85
   58.63  133.88      86  126.83   102.6  131.42  107.49  132.86  117.26  135.99
  122.14  137.43  127.03  138.65   136.8  140.78  141.69  141.48  146.57  141.69
  151.46  141.63  156.34  141.36  161.23   140.8  166.11  140.09     171  139.91
  180.21  140.96  184.82  141.41  194.03   141.7  203.24  141.78  207.84  141.72
#Mann= 3 ,-1 , 0
       0     .07       0   29.31     .04       0  146.57     .07       0
Bank Sta=29.31,146.57
XS Rating Curve= 0 ,0
Exp/Cntr=0.3,0.1

Type RM Length L Ch R = 1 ,11053.56,400.45,400.52,400.36
XS GIS Cut Line= 4
2988225.4669714413861322.4199134 2988226.125434713861267.7215319
2988228.18350144 13861096.7340132988228.5765452813861064.0870967
#Sta/Elev= 28
       0  140.65   24.86  140.54   39.78  140.37   44.76  140.63   49.73   140.7
    54.7  140.93   59.59  140.05   64.47  139.47   69.36  140.79   74.25  141.54
   79.13   141.6    83.5  140.95     133   125.8     137   125.7     142   125.8
  185.75  139.54   191.5  140.99  196.39  141.76  201.27  141.76  206.16   141.4
  211.05  140.68  215.93  139.61  220.82  139.14   225.7  139.93  230.37   140.8
  235.03  141.27  249.02  141.73  258.35   141.9
#Mann= 3 ,-1 , 0
       0     .07       0   79.13     .04       0  196.39     .07       0
Bank Sta=79.13,196.39
XS Rating Curve= 0 ,0
Exp/Cntr=0.3,0.1

Type RM Length L Ch R = 1 ,10653.05,300.95,301.34,301.43
XS GIS Cut Line= 5
2988625.10987294 13861386.453906 2988625.712890113861335.1039431
2988626.3762746213861278.62144452988628.3729897713861108.6329394
2988628.6725298613861083.1392239
#Sta/Elev= 30
       0  139.91   14.01  139.92   32.68   140.2   56.06  140.06   74.89  140.17
    79.6  140.23    84.3  140.39   93.72  140.51   98.43  140.67  103.13  140.62
   112.7  139.49  117.55  140.27  122.41  140.95  127.27  141.23  132.13  140.81
  136.29  139.87     183   125.6     187   125.4     191   125.7  239.17  139.75
  243.84   140.9   248.7  141.55  253.55  141.47  258.41  141.16  263.27  140.34
  268.13  139.17  272.98  139.23  277.84  139.79  282.09  140.11  303.34  140.44
#Mann= 3 ,-1 , 0
       0     .07       0  127.27     .04       0   248.7     .07       0
Bank Sta=127.27,248.7
XS Rating Curve= 0 ,0
Exp/Cntr=0.3,0.1

Type RM Length L Ch R = 1 ,10351.71,299.85,299.86,299.81
XS GIS Cut Line= 5
2988924.6378171913861434.44692032988926.1204257813861344.6239372
2988926.9990329413861291.39340062988929.7713371113861123.4163744
2988930.1991577713861097.4974629
#Sta/Elev= 30
       0  140.08   14.97  140.86   34.94  139.83   49.91  139.95   64.88  139.57
   74.86  140.37   79.85  140.54   89.84  140.15   99.51  140.75  104.35  140.43
  109.19  139.73  114.03  139.52  123.71  140.03  128.55   139.8  148.01  139.69
   157.9  140.54  162.84  140.71  167.78  140.67  172.72  140.23  176.26  139.48
     219   125.9     225   125.3     231   126.1  279.19  139.19  286.37  140.48
  291.31  140.62  296.25  140.37  306.13  138.97  319.71  139.36     337  139.19
#Mann= 3 ,-1 , 0
       0     .07       0  162.84     .04       0  291.31     .07       0
Bank Sta=162.84,291.31
XS Rating Curve= 0 ,0
Exp/Cntr=0.3,0.1

Type RM Length L Ch R = 1 ,10051.85,201.11,201.16,201.13
XS GIS Cut Line= 5
2989224.35342512 13861445.3789852989225.2638563713861389.0277198
2989225.8278316113861354.12162162989226.7034860313861299.9143809
2989229.6483620313861117.6332494
#Sta/Elev= 30
       0  140.01   23.48  139.86   32.88  140.05   42.27   139.5   46.97  139.59
   56.36   140.6   66.33  139.52   76.31  140.35   91.27  139.55  110.98  139.34
  120.84  139.51  135.63  139.45  150.41  138.88  155.34  139.23  160.26  139.94
  165.19  140.28  170.12  140.21  175.05  139.54  176.75  139.15     221   126.1
     227   125.2     232   125.8  279.93  139.57  283.44  140.32  288.37  140.78
  298.23   140.4  308.08  138.99  313.01  138.96  317.93  139.58  327.79  139.72
#Mann= 3 ,-1 , 0
       0     .07       0  165.19     .04       0  288.37     .07       0
#Block Obstruct= 1 ,-1
  325.75  327.79139.7402
Bank Sta=165.19,288.37
XS Rating Curve= 0 ,0
Exp/Cntr=0.3,0.1

Type RM Length L Ch R = 1 ,9850.69 ,555.64,554.98,553.73
XS GIS Cut Line= 5
2989425.3753327713861452.71131942989426.10695861  13861407.09166
2989426.8543324513861360.49201572989427.4173234413861325.3962854
2989430.6568182713861123.4806787
#Sta/Elev= 30
       0  139.52   13.69  140.27   22.81  139.74    36.5  139.73   45.63  140.64
   54.95  141.02   64.27  140.38   68.93  139.64   82.91  140.39   92.23  140.38
  105.39  139.21  122.94  139.42  132.26  138.65  142.11  138.57  151.96  137.74
  161.81  138.97  166.73  139.13  171.66  138.89  178.64  137.87     223   125.9
     227   125.2     233   125.7  280.02  138.79  284.94  139.79   294.8  140.04
  299.72  139.92  309.57  138.45   314.5  138.55  319.42  139.28  329.27  139.67
#Mann= 3 ,-1 , 0
       0     .07       0  166.73     .04       0   294.8     .07       0
#Block Obstruct= 1 ,-1
  325.93  329.27139.6739
Bank Sta=166.73,294.8
XS Rating Curve= 0 ,0
Exp/Cntr=0.3,0.1

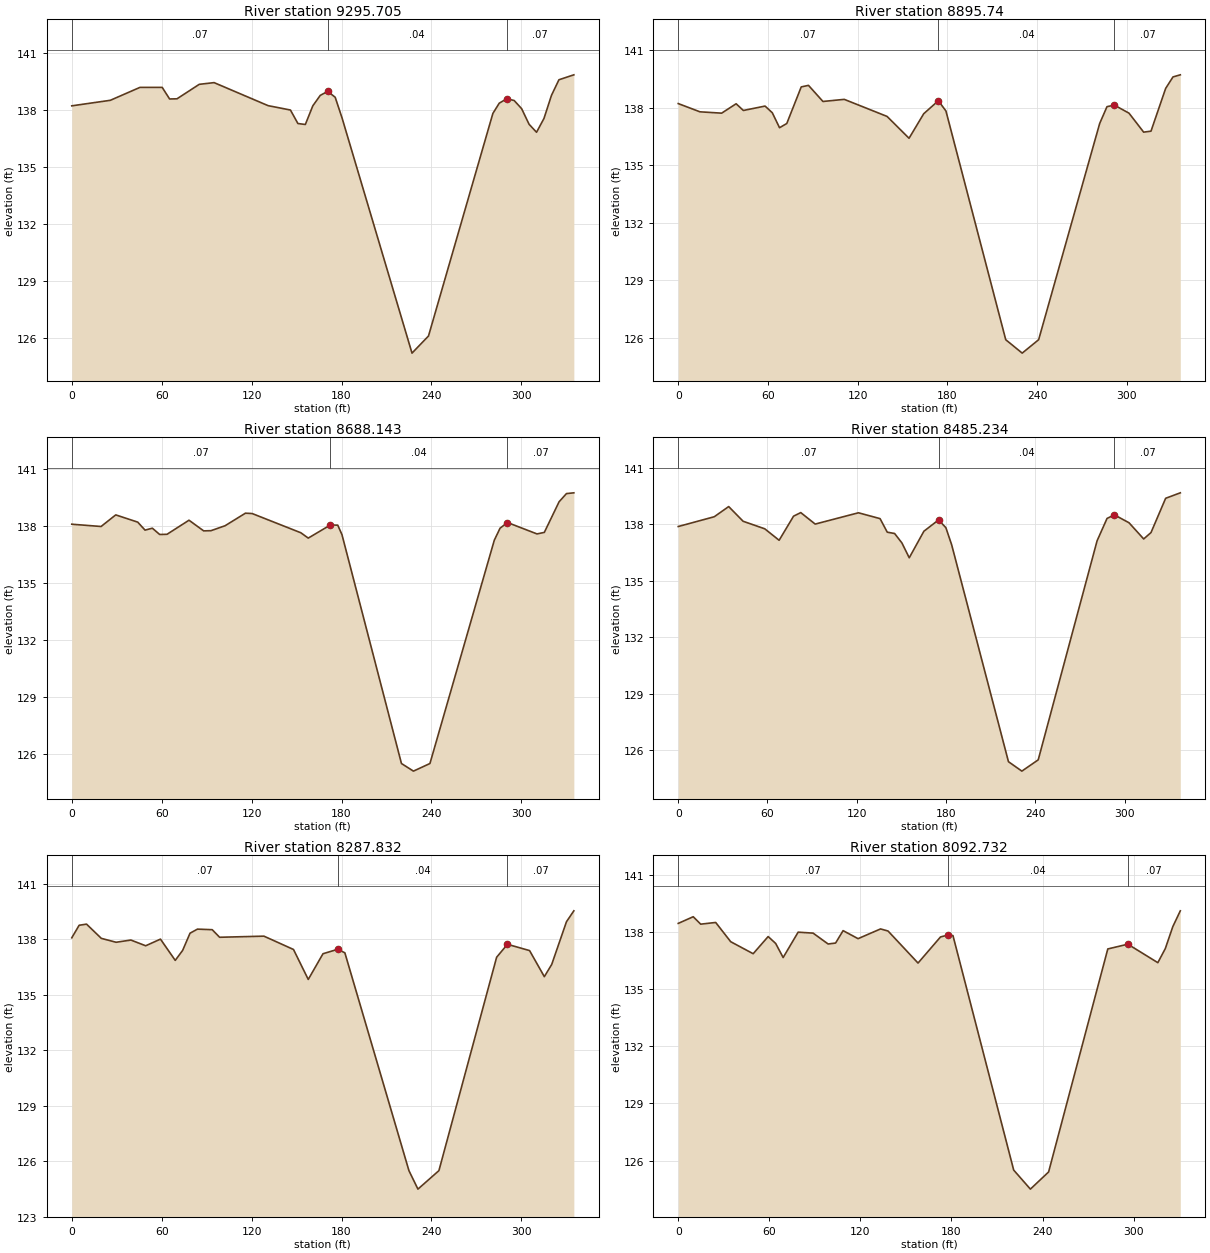
Type RM Length L Ch R = 1 ,9295.705,398.77,399.97,401.64
XS GIS Cut Line= 5
2989984.0809082813861473.09054382989984.0349766213861457.2716778
2989983.8049901913861378.14191482989983.7003316113861342.1242703
2989983.1068288513861138.1253344
#Sta/Elev= 30
       0   138.2   25.71  138.49   45.49  139.17   60.33  139.17   65.28  138.56
   70.22  138.57   85.06  139.33   94.95  139.42  130.97  138.21  145.89  137.98
  150.87  137.27  155.84  137.22  160.82   138.2   165.8  138.75  170.77  138.96
  175.75  138.65   180.3  137.57     227   125.2     238   126.1  280.95   137.8
  285.21  138.34  290.19  138.57  295.16  138.48  300.14  138.05  305.11  137.23
  310.09  136.81  315.06  137.54  320.04  138.75  325.02  139.57  334.97  139.83
#Mann= 3 ,-1 , 0
       0     .07       0  170.77     .04       0  290.19     .07       0
Bank Sta=170.77,290.19
XS Rating Curve= 0 ,0
Exp/Cntr=0.3,0.1

Type RM Length L Ch R = 1 ,8895.74 ,208.04,207.6,207.04
XS GIS Cut Line= 4
2990377.3793342713861487.43598752990379.8835943613861390.6937269
2990380.8658758613861352.74662442990386.0666528613861151.8139554
#Sta/Elev= 30
       0  138.22   14.52  137.79   29.03  137.72   38.71  138.21   43.55  137.86
   58.06  138.09    62.9  137.74   67.74  136.96   72.58  137.18   82.26  139.09
    87.1  139.17   96.77  138.33  111.01  138.44  139.64  137.55  154.34  136.41
  164.15  137.69  173.95  138.37  179.03  137.83     219   125.9     230   125.2
     241   125.9  281.81  137.18  286.71  138.06  291.61  138.14  301.42  137.72
  311.22  136.73  316.12  136.78  325.93  139.01  330.83  139.61  335.73  139.72
#Mann= 3 ,-1 , 0
       0     .07       0  173.95     .04       0  291.61     .07       0
Bank Sta=173.95,291.61
XS Rating Curve= 0 ,0
Exp/Cntr=0.3,0.1

Type RM Length L Ch R = 1 ,8688.143,202.9,202.91,202.93
XS GIS Cut Line= 4
2990587.0619857813861495.08426622990588.6305521913861397.3088712
2990589.3562725313861352.07142892990592.43631886 13861160.096091
#Sta/Elev= 30
       0  138.08   19.56  137.96   29.34  138.57      44  138.19   48.89  137.77
   53.78  137.87   58.67  137.54   63.56  137.55   78.23  138.29   88.01  137.73
    92.9  137.74  102.31     138  115.89  138.66  120.41  138.64  152.88  137.63
   157.8  137.35  172.57  138.04  177.49  138.03  180.31  137.53     220   125.5
     228   125.1     239   125.5  281.96  137.24   285.8  137.87  290.72  138.17
  310.42  137.57  315.34  137.65  325.19  139.26  330.11  139.69  335.03  139.73
#Mann= 3 ,-1 , 0
       0     .07       0  172.57     .04       0  290.72     .07       0
Bank Sta=172.57,290.72
XS Rating Curve= 0 ,0
Exp/Cntr=0.3,0.1

Type RM Length L Ch R = 1 ,8485.234,197.54,197.4,197.36
XS GIS Cut Line= 3
2990789.9093491113861502.4832015 2990792.132113713861361.9867634
2990795.2482491913861165.0114355
#Sta/Elev= 30
       0  137.89   24.23  138.41   33.92  138.95   43.61  138.17   58.14  137.77
   67.83  137.16   77.52  138.44   82.37  138.63   92.06  138.02  121.13  138.62
  135.67  138.31  140.51  137.59  145.44  137.52  150.36  137.02  155.29  136.23
  165.14  137.64  174.99  138.24  179.91  137.83  183.81  136.92     222   125.4
     231   124.9     242   125.5  281.56  137.13  288.26  138.32  293.19  138.51
  303.04  138.09  312.89  137.23  317.81  137.57  327.66  139.39  337.51  139.68
#Mann= 3 ,-1 , 0
       0     .07       0  174.99     .04       0  293.19     .07       0
Bank Sta=174.99,293.19
XS Rating Curve= 0 ,0
Exp/Cntr=0.3,0.1

Type RM Length L Ch R = 1 ,8287.832,192.79,195.1,192.61
XS GIS Cut Line= 3
2990987.49097495  13861509.689882990989.5867712813861366.6658878
2990992.4000858713861174.6862849
#Sta/Elev= 30
       0  138.09    4.93  138.77    9.86  138.83   19.73  138.06   29.59  137.85
   39.46  137.97   49.32  137.66   59.19  138.02   69.05  136.87   73.99  137.41
   78.92  138.34   83.85  138.56   93.72  138.53   98.65  138.12  128.24  138.18
  147.96  137.46  157.81  135.84  167.65  137.23   177.5  137.47  182.24  137.28
     225   125.5     231   124.5     245   125.5  283.52  137.04  290.73  137.74
   305.5   137.4  315.35  135.99  320.27  136.65  330.12  138.96  335.04  139.55
#Mann= 3 ,-1 , 0
       0     .07       0   177.5     .04       0  290.73     .07       0
Bank Sta=177.5,290.73
XS Rating Curve= 0 ,0
Exp/Cntr=0.3,0.1

Type RM Length L Ch R = 1 ,8092.732,190.72,191.54,192.39
XS GIS Cut Line= 2
2991180.2884896113861516.72234632991184.8107902713861185.9848188
#Sta/Elev= 30
       0  138.44    9.87  138.79   14.81   138.4   24.68  138.49   34.56  137.48
   49.37  136.85   59.24  137.75   64.18  137.39   69.12  136.65   78.99  137.98
   88.86  137.93   98.74  137.36  103.67  137.41  108.61  138.06  118.48  137.64
  133.29  138.15  138.23  138.04  157.98  136.36  172.79  137.73  177.73  137.83
     181   137.8     221   125.5     232   124.5     244   125.4     283   137.1
  296.21  137.35  315.96  136.38  320.89  137.12  325.83  138.27  330.77   139.1
#Mann= 3 ,-1 , 0
       0     .07       0  177.73     .04       0  296.21     .07       0
Bank Sta=177.73,296.21
XS Rating Curve= 0 ,0
Exp/Cntr=0.5,0.3

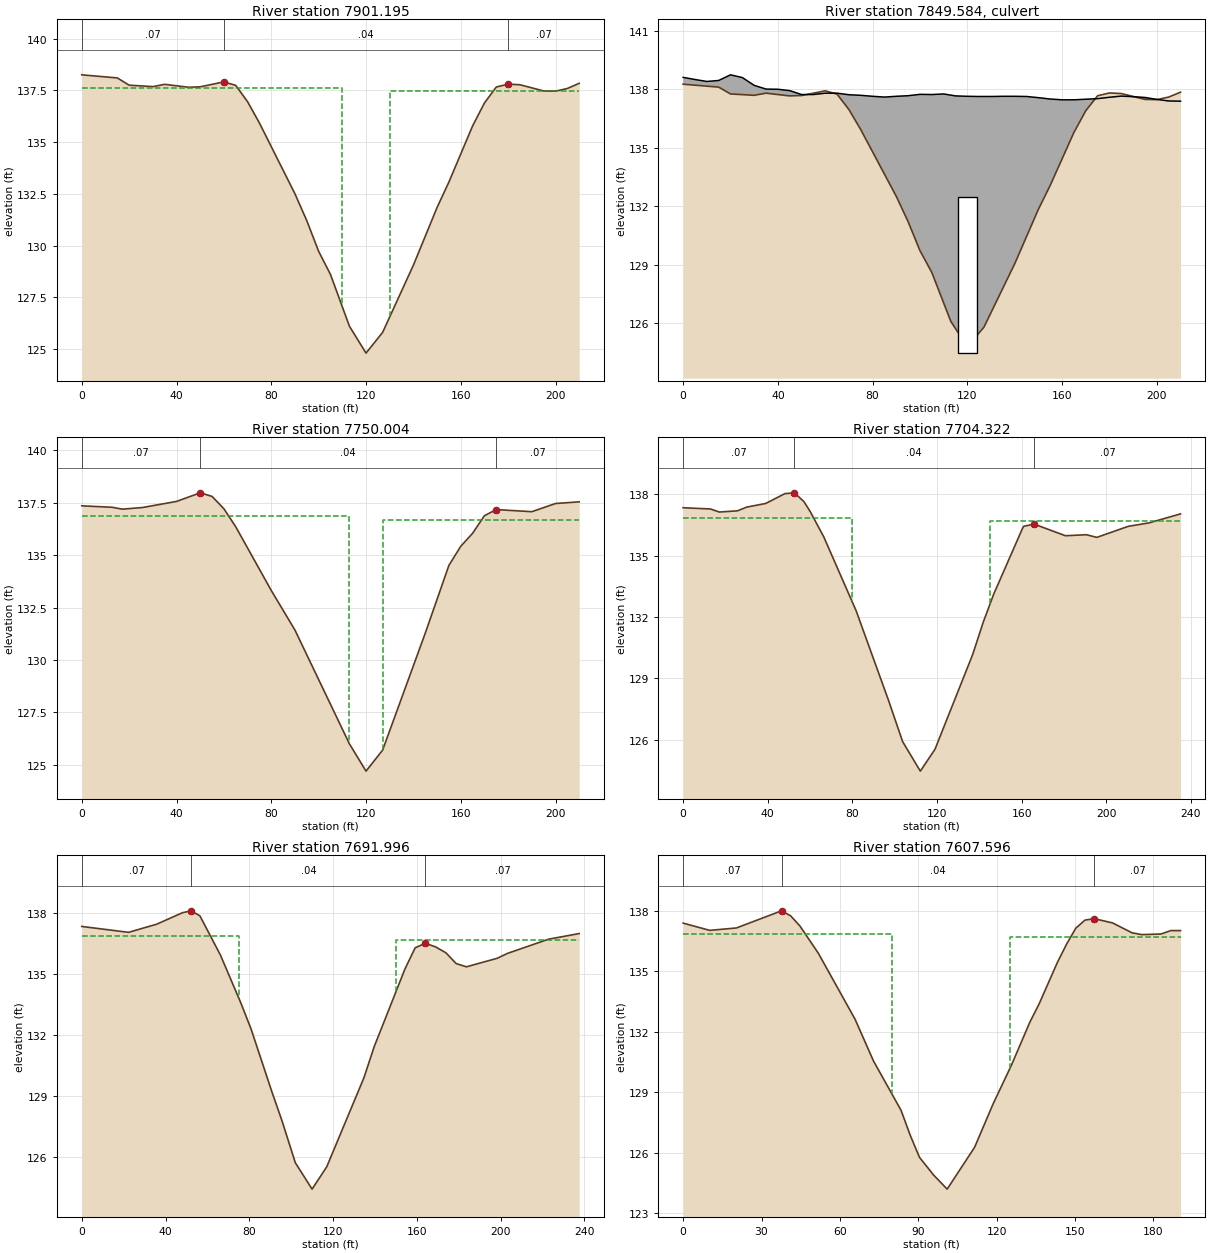
Type RM Length L Ch R = 1 ,7901.195,151.55,151.19,151.24
BEGIN DESCRIPTION:
Upstream Section - FUTURE PEEK RD
END DESCRIPTION:
Node Name=L
XS GIS Cut Line= 4
2991371.4741308513861406.75931162991372.3409270213861376.7718388
2991374.9409874413861286.80942032991377.5410478613861196.8470018
#Sta/Elev= 30
       0  138.25      15   138.1      20  137.75      30  137.68      35  137.79
  45.001  137.65      50  137.67      60  137.91  64.999  137.74      70  136.95
      75  135.92      90   132.5      95   131.2  99.999  129.72     105   128.6
     113   126.1 119.999   124.8 126.999   125.8     140  129.05     150  131.84
 154.999  133.07     165  135.78 170.001  136.89     175  137.66     180   137.8
     185  137.77     195  137.47     200  137.46     205  137.59 209.999  137.84
#Mann= 3 ,-1 , 0
       0     .07       0      60     .04       0     180     .07       0
#XS Ineff= 2 ,-1
       0     110  137.59     130 209.999  137.49
Permanent Ineff=
       F       F
Bank Sta=60,180
XS Rating Curve= 0 ,0
Exp/Cntr=0.5,0.3

Type RM Length L Ch R = 2 ,7849.584,,,
BEGIN DESCRIPTION:
FUTURE PEEK RD
END DESCRIPTION:
Node Name=FUTURE PEEK RD
Bridge Culvert--1,0,-1,-1, 0
Deck Dist Width WeirC Skew NumUp NumDn MinLoCord MaxHiCord MaxSubmerge Is_Ogee
11,140,2.6,0, 43, 43, , , 0.98, 0, 0,0,,
       0       5      10      15      20      25      30      35      40      45
      50      55      60      65      70      75      80      85      90      95
     100     105     110     115     120     125     130     135     140     145
     150     155     160     165     170     175     180     185     190     195
     200     205     210
   138.6  138.49  138.39  138.44  138.73  138.59  138.19     138  137.99  137.92
  137.72  137.72  137.79  137.79  137.71  137.68  137.63  137.59  137.63  137.66
  137.73  137.72  137.75  137.65  137.63  137.62  137.62  137.63  137.63  137.62
  137.56  137.49  137.45  137.45  137.48  137.51  137.58  137.64  137.61  137.57
  137.47  137.39  137.38
                                                                                
                                                                                
                                                                                
                                                                                
                        
       0       5      10      15      20      25      30      35      40      45
      50      55      60      65      70      75      80      85      90      95
     100     105     110     115     120     125     130     135     140     145
     150     155     160     165     170     175     180     185     190     195
     200     205     210
   138.6  138.49  138.39  138.44  138.73  138.59  138.19     138  137.99  137.92
  137.72  137.72  137.79  137.79  137.71  137.68  137.63  137.59  137.63  137.66
  137.73  137.72  137.75  137.65  137.63  137.62  137.62  137.63  137.63  137.62
  137.56  137.49  137.45  137.45  137.48  137.51  137.58  137.64  137.61  137.57
  137.47  137.39  137.38
                                                                                
                                                                                
                                                                                
                                                                                
                        
BR Coef=-1 , 0 , 0 ,, 0 ,,,0.8,-1,,0,
WSPro=,,,, 1 ,,,, 0 ,,,, 0 ,,,,-1 ,-1 ,-1 , 0 , 0 , 0 , 0 , 0
Culvert=2,8,8,140,0.015,0.5,1,10,1,124.47,120,124.17,120,Culvert #1  , 0 ,11
Culvert Bottom n=0.015
BC Design=,, 0 ,, 0 ,,,,,,
BC Use User HTab Curves=0
BC User HTab FreeFlow(D)= 0

Type RM Length L Ch R = 1 ,7750.004,1.79,45.68,82.37
BEGIN DESCRIPTION:
Downstream Section - FUTURE PEEK RD
END DESCRIPTION:
Node Name=K
XS GIS Cut Line= 4
 2991503.144471213861403.20616912991523.4685775313861381.1396122
2991526.0686379413861291.17719372991528.6686983613861201.2147752
#Sta/Elev= 23
       0  137.36   12.86  137.29   17.14   137.2   25.71  137.28      40  137.57
      50  137.98      55  137.81      60  137.22      65  136.36      80  133.32
      90  131.43     113     126     120   124.7     127   125.7     145  131.28
     155  134.52     160  135.43     165  136.05     170  136.89     175  137.18
     190  137.08     200  137.47     210  137.55
#Mann= 3 ,-1 , 0
       0     .07       0      50     .04       0     175     .07       0
#XS Ineff= 2 ,-1
       0     113  136.86     127     210  136.68
Permanent Ineff=
       F       F
Bank Sta=50,175
XS Rating Curve= 0 ,0
Exp/Cntr=0.5,0.3

Type RM Length L Ch R = 1 ,7704.322,10.69,12.33,14.06
XS GIS Cut Line= 4
2991504.8639559413861404.92565382991525.2070911113861382.8384277
2991525.9895698613861355.75875742991650.2750824413861228.3075688
#Sta/Elev= 28
       0  137.35   12.87  137.29   17.16  137.14   25.74   137.2   30.03  137.38
   39.06  137.56   48.09  138.04    52.6  138.08   57.12  137.65   60.09  137.16
   66.46  135.93   81.78  132.31   97.11  127.92  103.78   125.9  112.13  124.46
  119.06  125.53  136.89  130.17  141.84  131.74  146.77  133.11  160.22  136.29
  160.96  136.44  165.91  136.55  180.74  135.98  190.63  136.03  195.58   135.9
  210.41  136.44   220.3  136.61  235.14  137.05
#Mann= 3 ,-1 , 0
       0     .07       0    52.6     .04       0  165.91     .07       0
#XS Ineff= 2 ,-1
       0      80  136.86     145  235.14  136.68
Permanent Ineff=
       F       F
Bank Sta=52.6,165.91
XS Rating Curve= 0 ,0
Exp/Cntr=0.3,0.1

Type RM Length L Ch R = 1 ,7691.996,32.39,84.4,135.51
XS GIS Cut Line= 4
2991509.3429496113861409.4049756 2991533.579449713861383.0907238
 2991534.175905213861362.44640812991664.9699349413861237.1021706
#Sta/Elev= 27
       0  137.35   22.36  137.06   35.77  137.46   48.17  138.03    52.3  138.12
   56.43  137.87   66.22  135.94   76.01  133.57   80.91  132.28    90.7  129.23
    95.6  127.78     102   125.7     110   124.4     117   125.5  134.77  129.89
  139.66  131.42  154.35  135.25  159.25   136.3  164.14  136.52  169.04  136.34
  173.94  136.05  178.83  135.52  183.73  135.36  198.42  135.78  203.31  136.02
   222.9  136.72  237.59     137
#Mann= 3 ,-1 , 0
       0     .07       0    52.3     .04       0  164.14     .07       0
#XS Ineff= 2 ,-1
       0      75  136.86     150  237.59  136.68
Permanent Ineff=
       F       F
Bank Sta=52.3,164.14
XS Rating Curve= 0 ,0
Exp/Cntr=0.3,0.1

Type RM Length L Ch R = 1 ,7607.596,18.06,18.53,18.15
BEGIN DESCRIPTION:
Skewed Section (42 Deg.)
END DESCRIPTION:
XS GIS Cut Line= 5
2991513.5670225313861413.62904852991541.4747751113861383.3289123
2991631.4339127813861386.04117722991721.3930504513861388.7534421
2991745.9805996913861363.8446993
#Sta/Elev= 30
       0  137.39  10.203  137.03  20.407  137.15  37.655     138   41.17  137.75
  44.693  137.25   51.73   135.9  65.813  132.62  72.858  130.55  83.418   128.1
  86.933  126.86  90.456  125.77  95.866  124.89 101.068  124.19 111.576  126.27
 118.613  128.41 125.658  130.34 132.696  132.47 136.218  133.37 143.256  135.44
 146.779  136.35 150.301  137.14 153.816  137.54 157.339  137.61 164.376   137.4
 171.808  136.91 175.523  136.82 182.955  136.85 186.671  137.02 190.386  137.02
#Mann= 3 ,-1 , 0
       0     .07       0  37.655     .04       0 157.339     .07       0
#XS Ineff= 2 ,-1
       0      80  136.86     125  190.39  136.68
Permanent Ineff=
       F       F
Bank Sta=37.655,157.339
XS Rating Curve= 0 ,0
Skew Angle= 42
Exp/Cntr=0.5,0.3