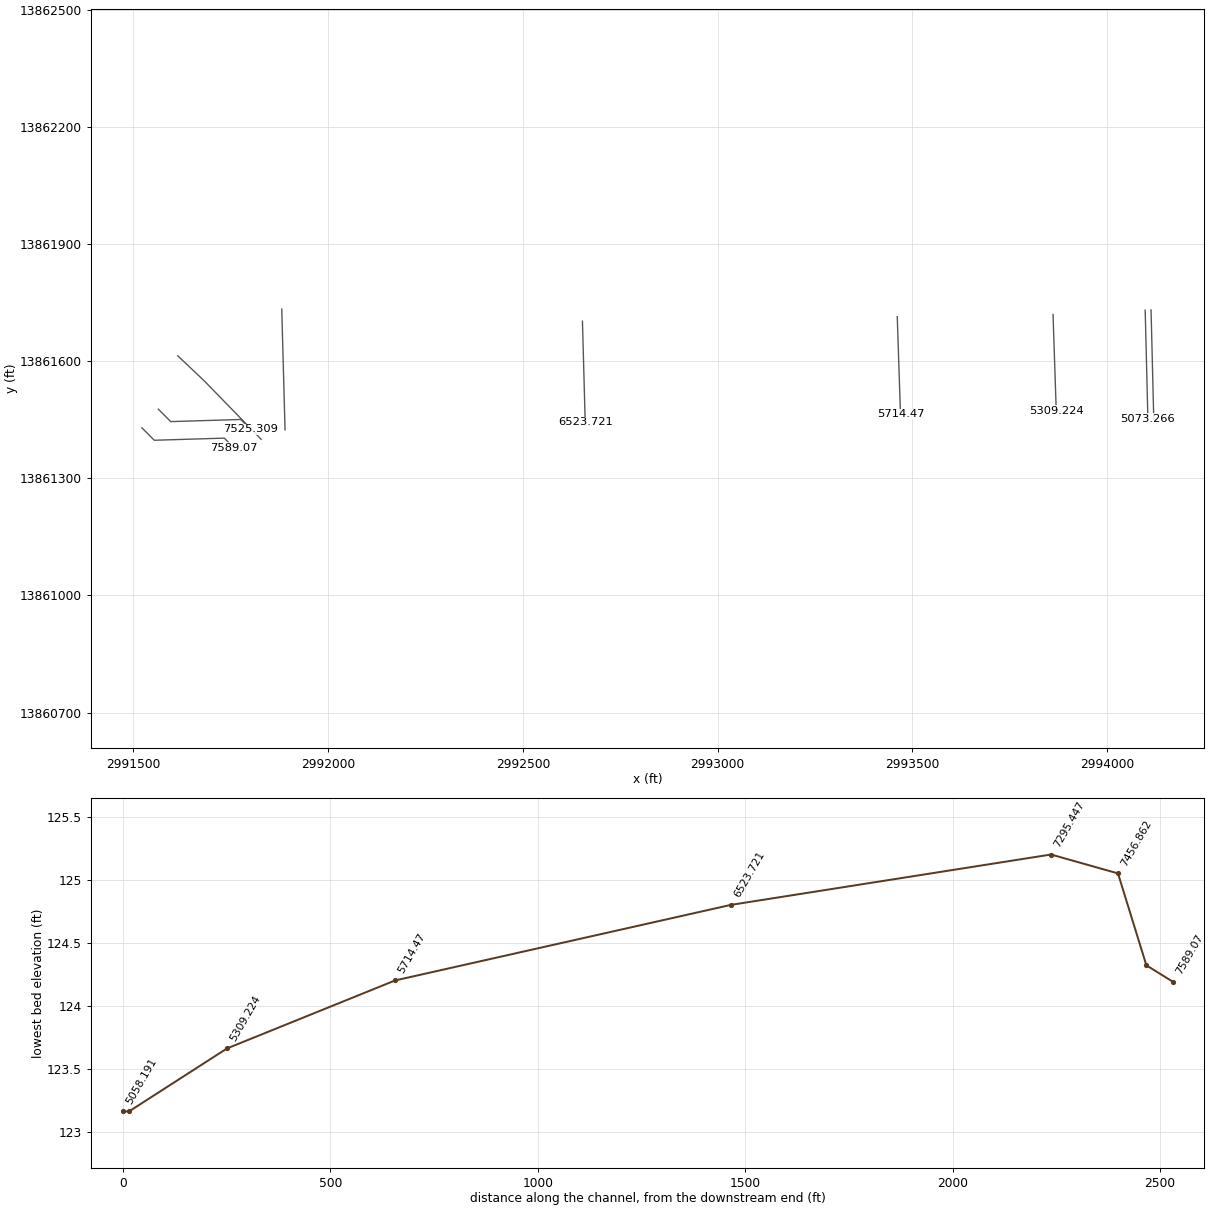
HEC-RAS study U101_08_00.prj: U101-08-00 2019 (Re-Study)

--- U101_08_00.g01 (geometry) --- (continued)

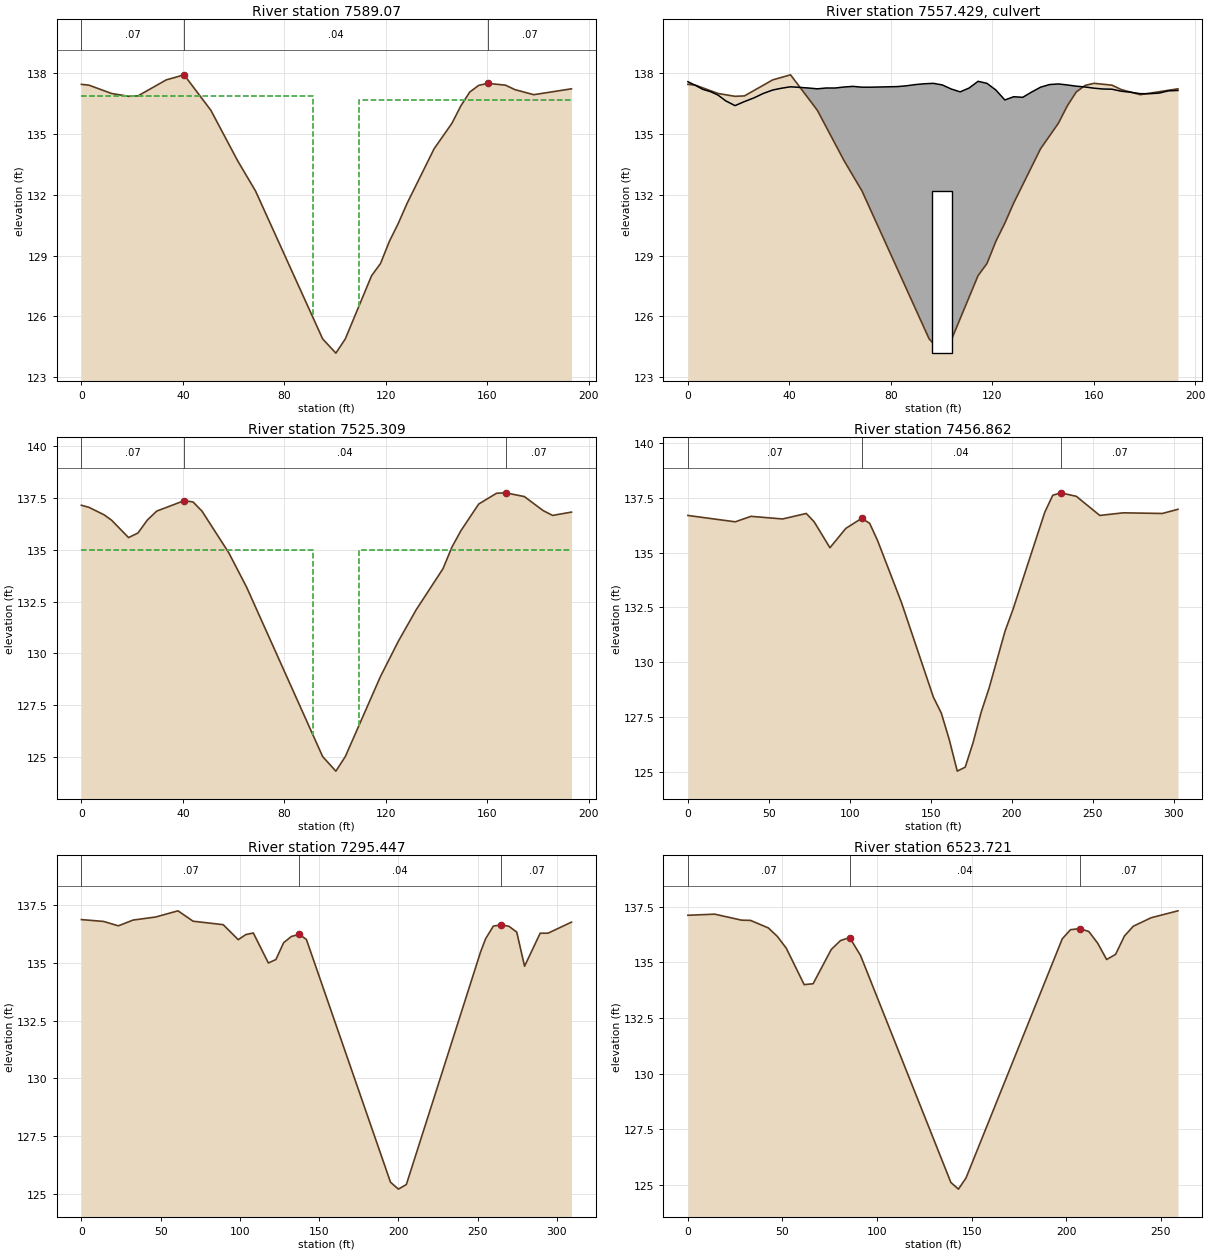
Type RM Length L Ch R = 1 ,7589.07 ,63.99,63.76,62.3
BEGIN DESCRIPTION:
Upstream Section - HP&L EASEMENT #2
END DESCRIPTION:
Node Name=J
XS GIS Cut Line= 6
2991521.8366910213861429.11294142991535.9790511913861414.9709094
2991553.6568373613861397.29345132991643.6159750213861400.0057162
 2991733.575112713861402.71798112991758.1626619413861377.8092383
#Sta/Elev= 28
       0  137.45   2.973  137.41   11.89     137  18.579  136.86  22.294  136.88
  33.442  137.67  40.479  137.92  51.039  136.17  61.599  133.68  68.644  132.19
  95.123  124.89 100.325  124.19  104.04  124.89 114.407  128.01 117.922  128.61
 121.445  129.71 124.967   130.6 128.482   131.6  139.05  134.27 146.087  135.53
  149.61  136.39  153.11  137.07 156.647   137.4  160.17   137.5 167.208  137.41
 170.923  137.19 178.355  136.94 193.218  137.23
#Mann= 3 ,-1 , 0
       0     .07       0  40.479     .04       0  160.17     .07       0
#XS Ineff= 2 ,-1
       0   91.32  136.86  109.32  193.22  136.68
Permanent Ineff=
       F       F
Bank Sta=40.479,160.17
XS Rating Curve= 0 ,0
Skew Angle= 42
Exp/Cntr=0.5,0.3

Type RM Length L Ch R = 2 ,7557.429,,,
BEGIN DESCRIPTION:
HP&L EASEMENT #2
42 deg. Skew
END DESCRIPTION:
Node Name=HP&L EASMT #2
Bridge Culvert--1,0,-1,-1, 0
Deck Dist Width WeirC Skew NumUp NumDn MinLoCord MaxHiCord MaxSubmerge Is_Ogee
4.5,47,2.6,42, 56, 56, , , 0.98, 0, 0,0,,
       0   2.973   5.945   8.918   11.89  14.863  18.579  22.294   26.01  29.726
  33.442  36.964  40.479  44.002  47.524  51.039  54.562  58.084  61.599  65.122
  68.644  72.167  75.682  79.204  82.727  86.242  89.764  93.287  96.802 100.325
 103.847 107.362 110.885 114.407 117.922 121.445 124.967 128.482 132.005 135.527
  139.05 142.565 146.087  149.61 153.125 156.647  160.17 163.685 167.208 170.923
 174.639 178.355  182.07 185.786 189.502 193.218
  137.58   137.4   137.2  137.09  136.92  136.64   136.4   136.6  136.78     137
  137.17  137.26  137.33   137.3  137.27  137.23  137.27  137.27  137.32  137.35
  137.31  137.31  137.32  137.33  137.34  137.38  137.44  137.48   137.5  137.42
  137.22  137.08  137.27   137.6   137.5  137.17  136.68  136.84  136.81  137.07
  137.31  137.44  137.47  137.42  137.36  137.32  137.26  137.22  137.21  137.11
  137.06  136.99  136.99  137.02  137.13  137.15
                                                                                
                                                                                
                                                                                
                                                                                
                                                                                
                                                
       0   2.973   5.945   8.918   11.89  14.863  18.579  22.294   26.01  29.726
  33.442  36.964  40.479  44.002  47.524  51.039  54.562  58.084  61.599  65.122
  68.644  72.167  75.682  79.204  82.727  86.242  89.764  93.287  96.802 100.325
 103.847 107.362 110.885 114.407 117.922 121.445 124.967 128.482 132.005 135.527
  139.05 142.565 146.087  149.61 153.125 156.647  160.17 163.685 167.208 170.923
 174.639 178.355  182.07 185.786 189.502 193.218
  137.58   137.4   137.2  137.09  136.92  136.64   136.4   136.6  136.78     137
  137.17  137.26  137.33   137.3  137.27  137.23  137.27  137.27  137.32  137.35
  137.31  137.31  137.32  137.33  137.34  137.38  137.44  137.48   137.5  137.42
  137.22  137.08  137.27   137.6   137.5  137.17  136.68  136.84  136.81  137.07
  137.31  137.44  137.47  137.42  137.36  137.32  137.26  137.22  137.21  137.11
  137.06  136.99  136.99  137.02  137.13  137.15
                                                                                
                                                                                
                                                                                
                                                                                
                                                                                
                                                
BR Coef=-1 , 0 , 0 ,, 0 ,,,0.8,-1,,0,
WSPro=,,,, 1 ,,,, 0 ,,,, 0 ,,,,-1 ,-1 ,-1 , 0 , 0 , 0 , 0 , 0
Culvert=2,8,8,47,0.015,0.5,1,10,1,124.19,100.32,124.32,100.32,Culvert #1  , 0 ,4.5
Culvert Bottom n=0.015
BC Design=,, 0 ,, 0 ,,,,,,
BC Use User HTab Curves=0
BC User HTab FreeFlow(D)= 0

Type RM Length L Ch R = 1 ,7525.309,122.59,68.45,18.63
BEGIN DESCRIPTION:
Downstream Section - HP&L EASEMENT #2
END DESCRIPTION:
XS GIS Cut Line= 6
2991564.0557666913861476.86907952991578.1981268713861462.7270474
2991595.8759130213861445.04958942991685.8350506913861447.7618543
2991775.7941883713861450.4741192 2991800.381737613861425.5653764
#Sta/Elev= 29
       0  137.15   2.973  137.05   8.918  136.69   11.89  136.43  18.579  135.59
  22.294  135.81   26.01  136.44  29.726  136.87  40.479  137.37  44.002  137.31
  47.524  136.87  58.084  134.86  65.122   133.2  95.123  125.02 100.325  124.32
  104.04  125.02 117.922  128.89 124.967  130.59 132.005  132.11 142.565  134.09
 146.087  135.13  149.61  135.92 156.647  137.21 163.685  137.73 167.208  137.75
 174.639  137.57  182.07  136.89 185.786  136.66 193.218  136.82
#Mann= 3 ,-1 , 0
       0     .07       0  40.479     .04       0 167.208     .07       0
#XS Ineff= 2 ,-1
       0   91.32     135  109.32  193.22     135
Permanent Ineff=
       F       F
Bank Sta=40.479,167.208
XS Rating Curve= 0 ,0
Skew Angle= 42
Exp/Cntr=0.5,0.3

Type RM Length L Ch R = 1 ,7456.862,204.65,161.41,121.87
Node Name=I
XS GIS Cut Line= 4
2991613.9378847813861613.54564342991681.32685761 13861550.028382
2991777.4870983713861451.54957642991828.0539263613861399.7635907
#Sta/Elev= 30
       0  136.69   29.24   136.4   38.99  136.65   58.49  136.53   73.11  136.78
   77.98   136.4   87.73  135.22   97.52   136.1  107.35  136.56  112.27  136.33
  117.18  135.54  131.93  132.72  151.59  128.42  156.51  127.69  161.43  126.48
  166.34  125.05  171.26  125.23  176.17  126.36  181.09  127.73     186  128.83
  195.84  131.42  200.75  132.41  220.41  136.84  225.33  137.61  230.25  137.72
   239.9  137.56  254.37  136.69  268.85  136.81  292.97  136.78  302.62  136.97
#Mann= 3 ,-1 , 0
       0     .07       0  107.35     .04       0  230.25     .07       0
Bank Sta=107.35,230.25
XS Rating Curve= 0 ,0
Exp/Cntr=0.3,0.1

Type RM Length L Ch R = 1 ,7295.447,771.11,771.73,771.04
XS GIS Cut Line= 5
2991880.9868913613861733.14087672991882.1319021913861691.2197007
2991884.3369502713861610.48725062991888.3507217813861463.5420064
2991889.4284755313861424.0857205
#Sta/Elev= 30
       0  136.88   13.98   136.8    23.3  136.61   32.62  136.86   46.69  136.99
   60.94  137.26   70.44  136.81   89.44  136.66   98.95  136.01   103.7  136.23
  108.45   136.3  117.95     135   122.7  135.15   127.6  135.88   132.5  136.15
   137.4  136.24  141.94  136.02     195   125.5     200   125.2     205   125.4
  251.83  135.48     255  136.05   259.9   136.6   264.8  136.65   269.7  136.59
  274.63  136.34  279.57  134.86  289.43  136.29  294.37  136.29  309.17  136.77
#Mann= 3 ,-1 , 0
       0     .07       0   137.4     .04       0   264.8     .07       0
Bank Sta=137.4,264.8
XS Rating Curve= 0 ,0
Exp/Cntr=0.3,0.1

Type RM Length L Ch R = 1 ,6523.721,808.87,809.25,809.47
XS GIS Cut Line= 4
2992653.0926306113861702.17112242992655.0434141213861631.2877339
2992658.9226714413861490.34116542992660.21860062 13861443.260879
#Sta/Elev= 27
       0  137.12   14.18  137.17   28.36   136.9   33.09  136.89   42.55  136.55
   47.27  136.17      52  135.64   61.46     134   66.18  134.04   75.77  135.58
   80.63  135.98    85.5  136.12   91.26  135.31     139   125.1     143   124.8
     147   125.3  197.87  136.06  202.19  136.47  207.05  136.52  211.91  136.39
  216.62  135.86  221.33  135.13  226.04  135.36  230.75  136.19  235.46  136.63
  244.88  137.01  259.01  137.32
#Mann= 3 ,-1 , 0
       0     .07       0    85.5     .04       0  207.05     .07       0
Bank Sta=85.5,207.05
XS Rating Curve= 0 ,0
Exp/Cntr=0.3,0.1

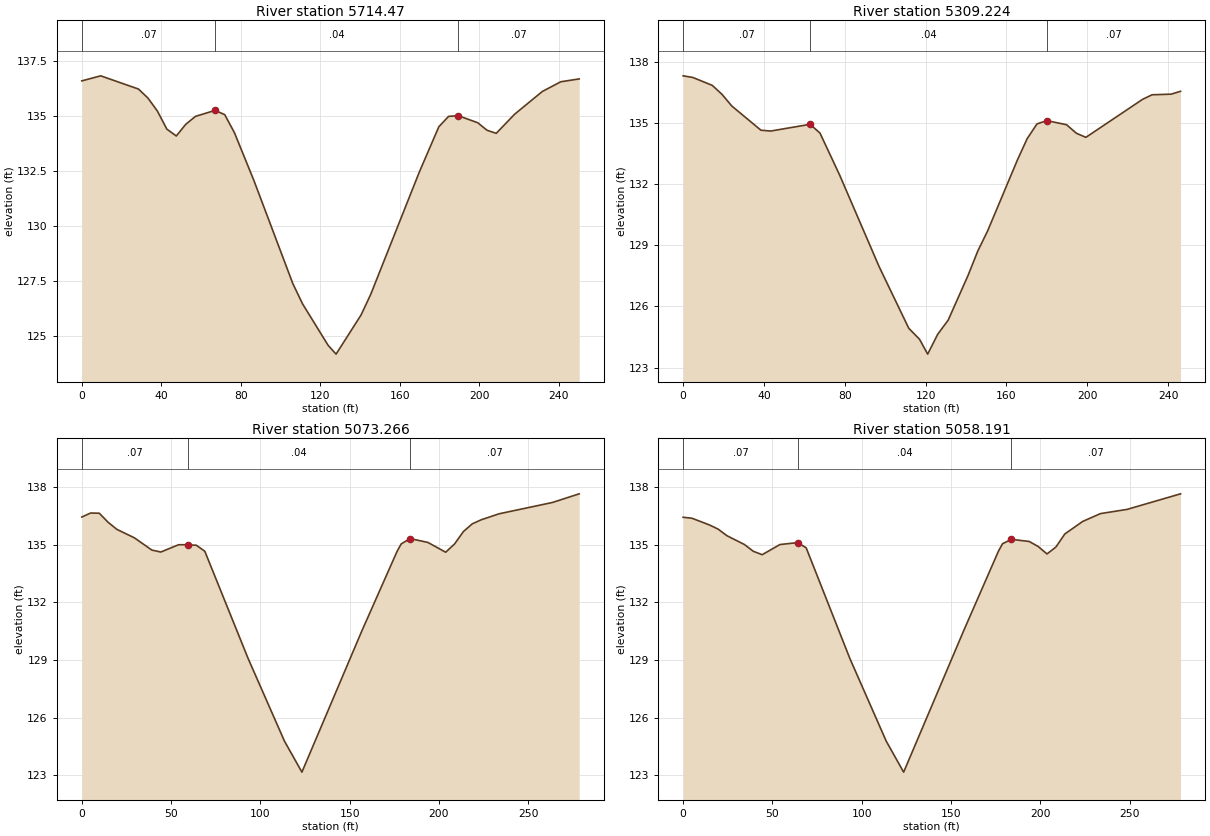
Type RM Length L Ch R = 1 ,5714.47 ,400.01,405.25,400
XS GIS Cut Line= 4
2993461.4414076113861713.65338292993463.1887794413861661.3404953
2993468.0962499413861514.42248212993469.8006428613861463.4006025
#Sta/Elev= 30
       0   136.6    9.52  136.83   28.55  136.23   33.31  135.82   38.07  135.23
   42.83  134.41   47.58   134.1   52.34  134.63   57.24  134.99   67.04  135.26
   71.94  135.07   76.84  134.25   86.64  132.08  106.24   127.4  111.14  126.48
     124   124.6     128   124.2  140.54  125.97  145.44  126.91  169.94  132.47
  179.74  134.52  184.64  134.99  189.54  135.02  199.34   134.7  203.98  134.36
  208.62  134.22  217.91  135.09  231.83  136.12  241.11  136.56  250.39  136.69
#Mann= 3 ,-1 , 0
       0     .07       0   67.04     .04       0  189.54     .07       0
Bank Sta=67.04,189.54
XS Rating Curve= 0 ,0
Exp/Cntr=0.3,0.1

Type RM Length L Ch R = 1 ,5309.224,236.3,235.96,235.37
XS GIS Cut Line= 4
2993861.4747282713861719.33578622993862.9209196113861676.0379725
2993867.9714344413861524.84208072993869.6915753613861473.3487453
#Sta/Elev= 30
       0  137.32    4.81  137.24   14.44  136.85   19.25  136.41   24.07  135.84
   38.51  134.65   43.32  134.61   62.84  134.94   67.72  134.51   77.48  132.44
      97  127.95  111.64  124.93  116.97  124.39     121  123.66     126  124.64
  131.16  125.33  140.92  127.51   145.8  128.72  150.68  129.71  165.32  133.17
   170.2  134.23  175.08  134.96  179.96  135.12  189.72  134.92   194.6   134.5
  199.29   134.3  227.39  136.17  232.07  136.39  241.44  136.42  246.12  136.56
#Mann= 3 ,-1 , 0
       0     .07       0   62.84     .04       0  179.96     .07       0
Bank Sta=62.84,179.96
XS Rating Curve= 0 ,0
Exp/Cntr=0.3,0.1

Type RM Length L Ch R = 1 ,5073.266,15.07,15.07,15.07
XS GIS Cut Line= 3
2994098.0415123613861730.3882575 2994099.097940713861691.1321024
2994105.0362490313861451.9071872
#Sta/Elev= 28
       0  136.44    4.91  136.65    9.82  136.64   14.73  136.17   19.64   135.8
   29.45  135.36   39.27  134.72   44.26  134.62   54.23     135   59.21     135
    64.2  134.97    68.9  134.66   93.14  129.08  113.53  124.77  123.28  123.16
  156.74  130.49  176.56  134.65  178.86  135.04  183.85  135.32  193.82  135.12
  203.79  134.61  208.77  135.04  213.76  135.69  218.74  136.09  223.73   136.3
   233.7  136.61  263.61   137.2  278.57  137.65
#Mann= 3 ,-1 , 0
       0     .07       0   59.21     .04       0  183.85     .07       0
Bank Sta=59.21,183.85
XS Rating Curve= 0 ,0
Exp/Cntr=0.3,0.1

Type RM Length L Ch R = 1 ,5058.191,166.54,167.44,168.02
BEGIN DESCRIPTION:
Upstream of Confluence with U201-07-01
END DESCRIPTION:
XS GIS Cut Line= 3
2994113.1015216113861730.99061852994114.1579499413861691.7344634
2994120.0962582813861452.5095482
#Sta/Elev= 27
       0  136.43    4.91  136.38   14.73  136.03   19.64  135.81   24.54  135.47
   34.36  135.01   39.27  134.66   44.26  134.48   54.23  135.01    64.2  135.11
   68.91  134.84   93.37  129.08  113.76  124.77   123.5  123.16  156.97  130.49
  176.62  134.67  178.86  135.05  183.85  135.28  193.82  135.17   198.8  134.91
  203.79  134.52  208.77  134.88  213.76  135.56  223.73  136.21   233.7  136.62
  248.66  136.84  278.57  137.65
#Mann= 3 ,-1 , 0
       0     .07       0    64.2     .04       0  183.85     .07       0
Bank Sta=64.2,183.85
XS Rating Curve= 0 ,0
Exp/Cntr=0.3,0.1