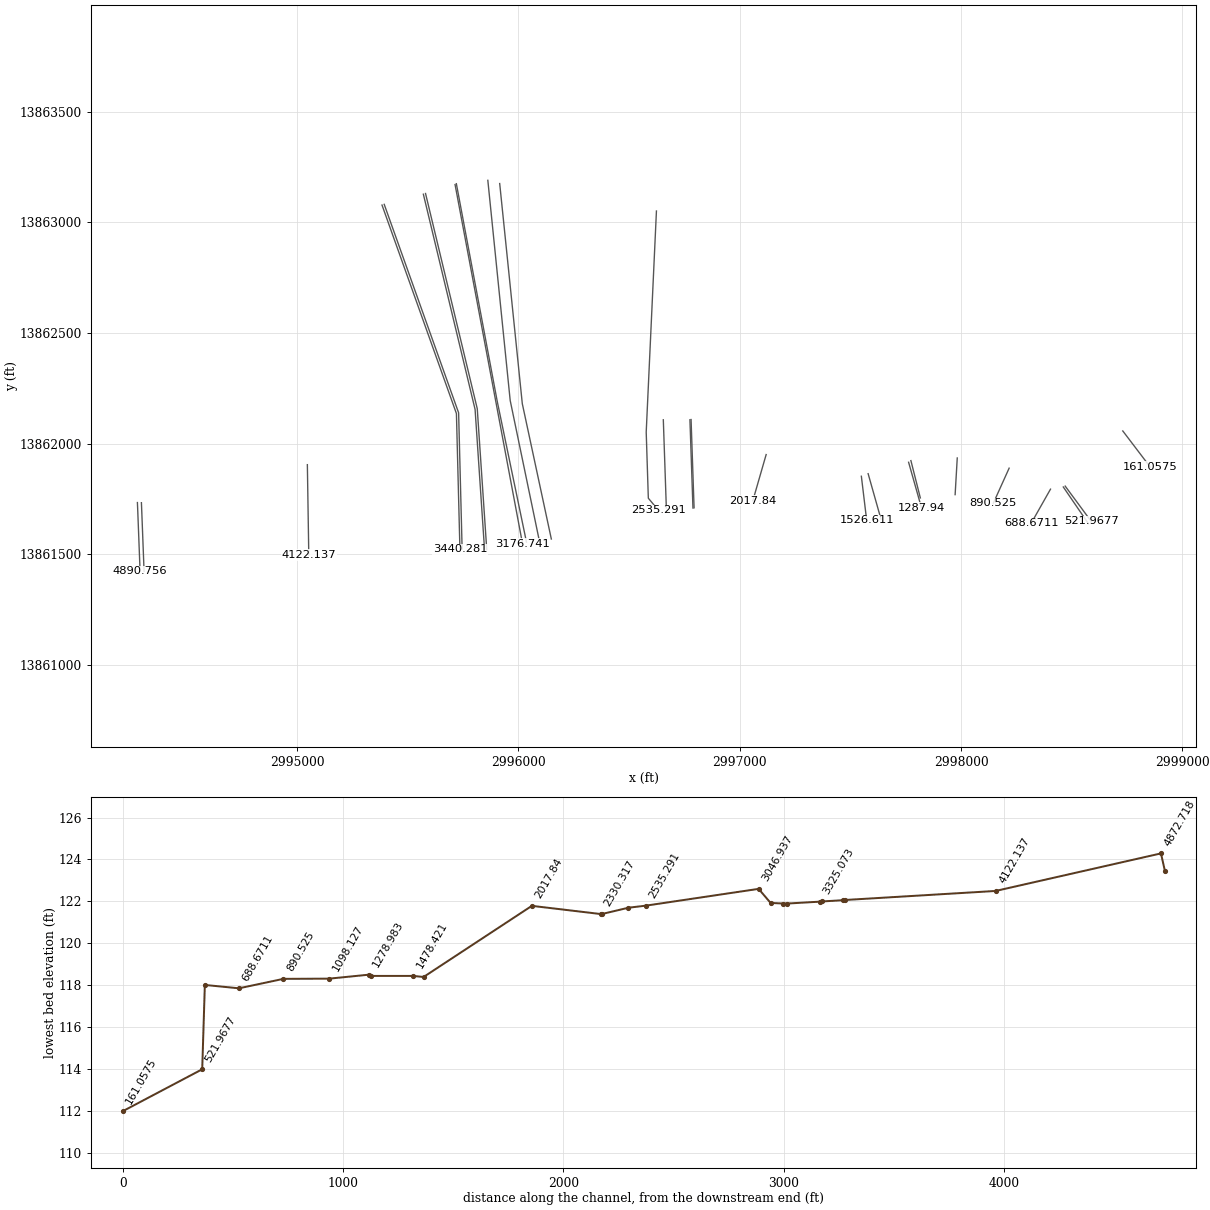
HEC-RAS study U101_08_00.prj: U101-08-00 2019 (Re-Study)

--- U101_08_00.g01 (geometry) --- (continued)

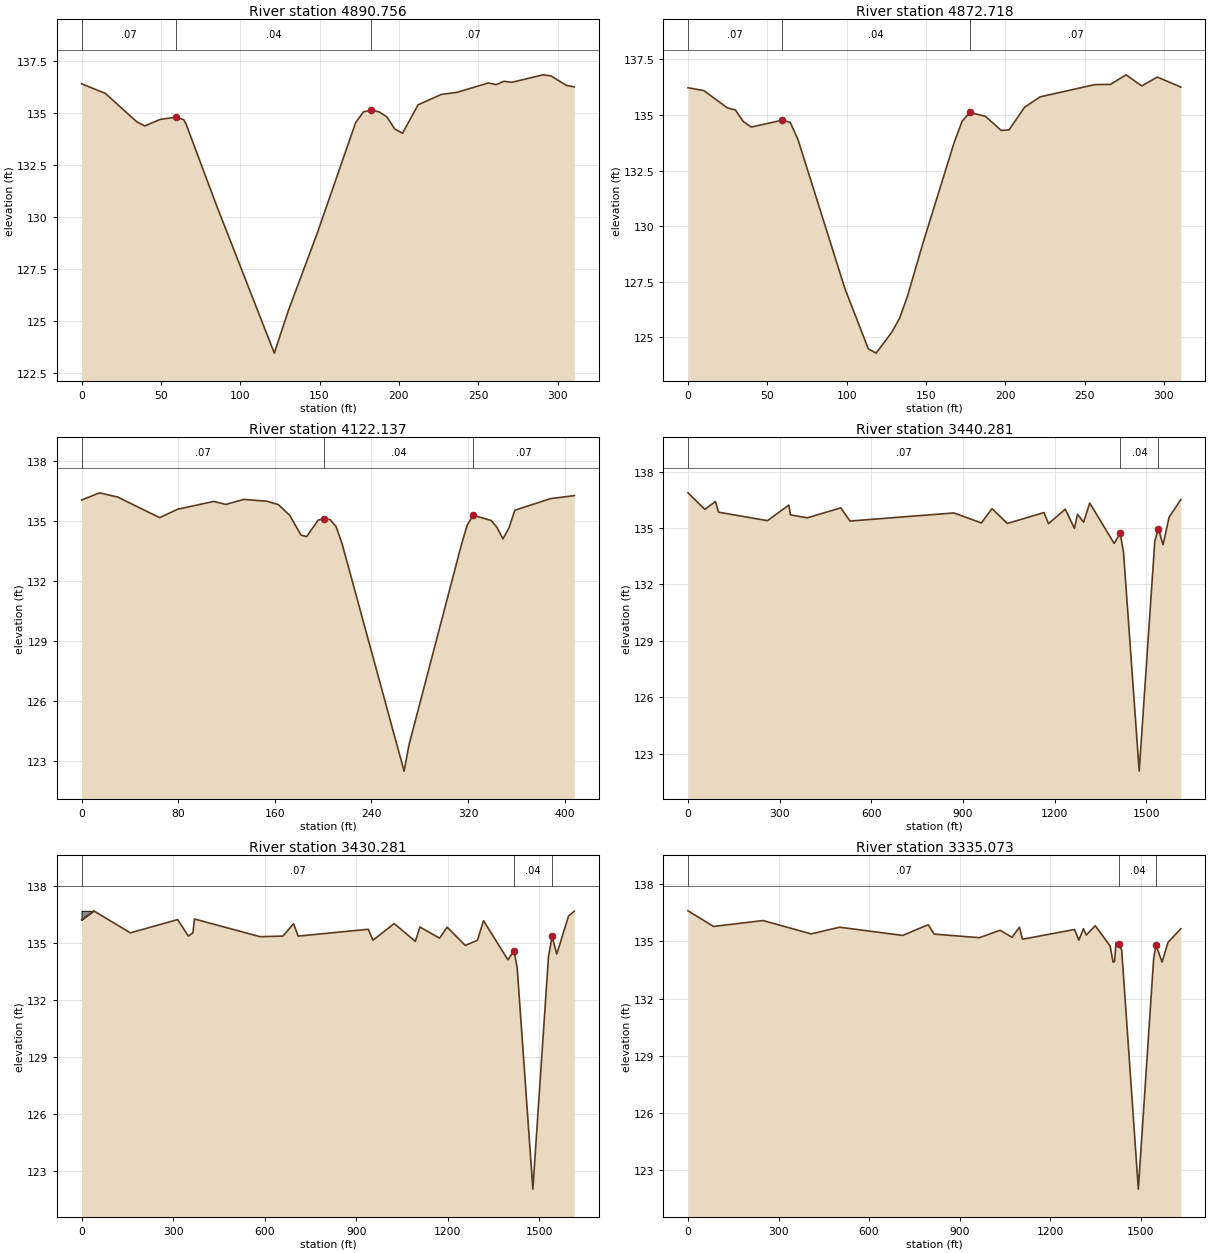
Type RM Length L Ch R = 1 ,4890.756,18.04,18.04,18.04
BEGIN DESCRIPTION:
Downstream of Confluence with U201-07-01
END DESCRIPTION:
Node Name=INFL U201-07-01
XS GIS Cut Line= 3
2994278.68780461 13861733.9453372994280.3193630313861694.1524376
2994290.7307595313861423.5873619
#Sta/Elev= 30
       0   136.4   14.93  135.94   34.85  134.57   39.83  134.37   49.67  134.69
   59.52  134.79   64.44  134.67    65.7   134.5   85.08  130.55  121.51  123.45
  130.23  125.47  148.87  129.28  172.75  134.53  177.67  135.05  182.59  135.13
  187.52  135.05  192.44  134.81  197.36  134.23  202.29  134.02  212.13  135.39
   226.9  135.89  236.75  135.99  256.44  136.44  261.36  136.36  266.28  136.52
  271.21  136.47   290.9  136.83  295.82  136.78  305.67  136.32  310.59  136.25
#Mann= 3 ,-1 , 0
       0     .07       0   59.52     .04       0  182.59     .07       0
Bank Sta=59.52,182.59
XS Rating Curve= 0 ,0
Exp/Cntr=0.3,0.1

Type RM Length L Ch R = 1 ,4872.718,750.88,750.58,748.45
XS GIS Cut Line= 3
2994296.75961886 13861733.3429762994298.3911772813861693.5500766
2994308.8025737713861422.9850009
#Sta/Elev= 30
       0  136.23    9.96   136.1   24.89  135.32   29.87  135.23   34.85  134.71
   39.83  134.46   59.52  134.77   64.44  134.67   69.36  133.89    98.9  127.19
  113.67  124.48  118.59  124.29  128.44  125.23  133.36  125.86  138.29  126.84
  148.13  129.25  167.82  133.78  172.75  134.72  177.67  135.12  187.52  134.94
  197.36  134.31  202.29  134.33  212.13  135.35  221.98  135.82  256.44  136.37
  266.28  136.38  276.13  136.81  285.98  136.31  295.82  136.71  310.59  136.26
#Mann= 3 ,-1 , 0
       0     .07       0   59.52     .04       0  177.67     .07       0
Bank Sta=59.52,177.67
XS Rating Curve= 0 ,0
Exp/Cntr=0.3,0.1

Type RM Length L Ch R = 1 ,4122.137,681.25,681.86,682.35
Node Name=H
XS GIS Cut Line= 5
2995046.4680931913861905.15135942995048.7410545213861760.9508604
2995049.4782577813861714.18422172995051.8109302813861566.2025623
2995052.8968861113861497.3034219
#Sta/Elev= 30
       0  136.05   14.92  136.41   29.84   136.2   64.65  135.17   79.57  135.59
  109.41  135.98  119.35  135.83  134.27  136.08  153.57  135.99  162.93  135.82
  172.28  135.29  181.64   134.3  186.31  134.22  195.92  135.05  200.86  135.12
  205.79  135.07  210.72  134.72  215.66  133.87     267   122.5     271   123.8
  314.32  133.79  319.26   134.8  324.19  135.29  338.99  135.03  343.91  134.68
  348.84  134.11  353.76  134.65  358.68  135.54  388.21  136.12   407.9  136.27
#Mann= 3 ,-1 , 0
       0     .07       0  200.86     .04       0  324.19     .07       0
Bank Sta=200.86,324.19
XS Rating Curve= 0 ,0
Exp/Cntr=0.3,0.1

Type RM Length L Ch R = 1 ,3440.281,10,10,10
XS GIS Cut Line= 5
2995383.7144659513863077.93641542995719.8660246113862136.1285878
2995726.9398293613861861.66096092995734.66914462 13861561.760642
2995735.6484733713861523.7649831
#Sta/Elev= 30
       0  136.87      55  135.99      90  136.41     100  135.84     260  135.39
     330  136.22     335   135.7     390  135.54     500  136.07     530  135.37
     870   135.8     960  135.27     995  136.03 1044.93  135.24 1164.74  135.82
 1179.71  135.23 1234.62     136 1264.57  134.98 1274.56  135.73 1294.56  135.31
 1314.56  136.33 1394.56  134.18 1414.56  134.72  1425.2   133.7 1476.52  122.07
 1527.63  134.31 1539.56  134.95 1554.56  134.11 1574.56  135.58 1612.57  136.51
#Mann= 3 , 0 , 0
       0     .07       0 1414.56     .04       0 1539.56     .07       0
Bank Sta=1414.56,1539.56
XS Rating Curve= 0 ,0
Exp/Cntr=0.3,0.1

Type RM Length L Ch R = 1 ,3430.281,92.96,95.21,97.36
BEGIN DESCRIPTION:
Upstream of Confluence with U201-08-01
END DESCRIPTION:
XS GIS Cut Line= 5
2995393.6330812713863081.22676322995729.7846399413862139.4189355
2995736.9365285313861861.91850632995744.6658437713861562.0181874
2995745.6336896113861524.4598636
#Sta/Elev= 30
       0  136.23      40  136.71     160  135.55     315  136.25     350  135.38
     365  135.55     370  136.28     585  135.35     660  135.38     695  136.03
     710  135.38     940  135.74     955  135.16 1024.79  136.04 1094.18   135.1
 1109.05  135.86  1173.5  135.27 1198.28  135.85 1257.76  134.89 1297.59  135.16
 1317.59  136.19 1397.59  134.13 1417.59  134.62 1427.95   133.7 1479.27  122.06
 1530.59  134.31 1542.59  135.36 1557.59  134.43 1596.38  136.44 1615.16  136.69
#Mann= 3 , 0 , 0
       0     .07       0 1417.59     .04       0 1542.59     .07       0
#Block Obstruct= 2 , 0
       0      40  136.71               0
Bank Sta=1417.59,1542.59
XS Rating Curve= 0 ,0
Exp/Cntr=0.3,0.1

Type RM Length L Ch R = 1 ,3335.073,10,10,10
BEGIN DESCRIPTION:
Downstream of Confluence with U201-08-01
END DESCRIPTION:
Node Name=OVFL U201-08-01
XS GIS Cut Line= 5
2995570.5270844413863126.98487382995804.2005016113862154.6695612
2995823.7519716913861864.65701792995843.9310651913861565.3364223
2995846.7867025313861522.9805358
#Sta/Elev= 30
       0   136.6   84.58  135.78  248.76  136.09  407.96  135.39  502.49  135.74
  711.44  135.31  796.02  135.87  815.92  135.38  965.17  135.19 1034.49  135.58
  1073.9  135.21 1098.53  135.74 1108.39  135.11 1280.82  135.62 1295.59  135.06
 1310.34  135.66 1320.18  135.33 1349.69  135.82 1398.87  134.76  1408.7  133.91
 1413.62  133.93 1418.54  134.94 1428.38  134.86 1437.32  134.54 1492.46     122
 1543.32  134.11 1551.33   134.8    1571  133.91 1590.67  134.94 1633.12  135.66
#Mann= 3 , 0 , 0
       0     .07       0 1428.38     .04       0 1551.33     .07       0
Bank Sta=1428.38,1551.33
XS Rating Curve= 0 ,0
Exp/Cntr=0.3,0.1

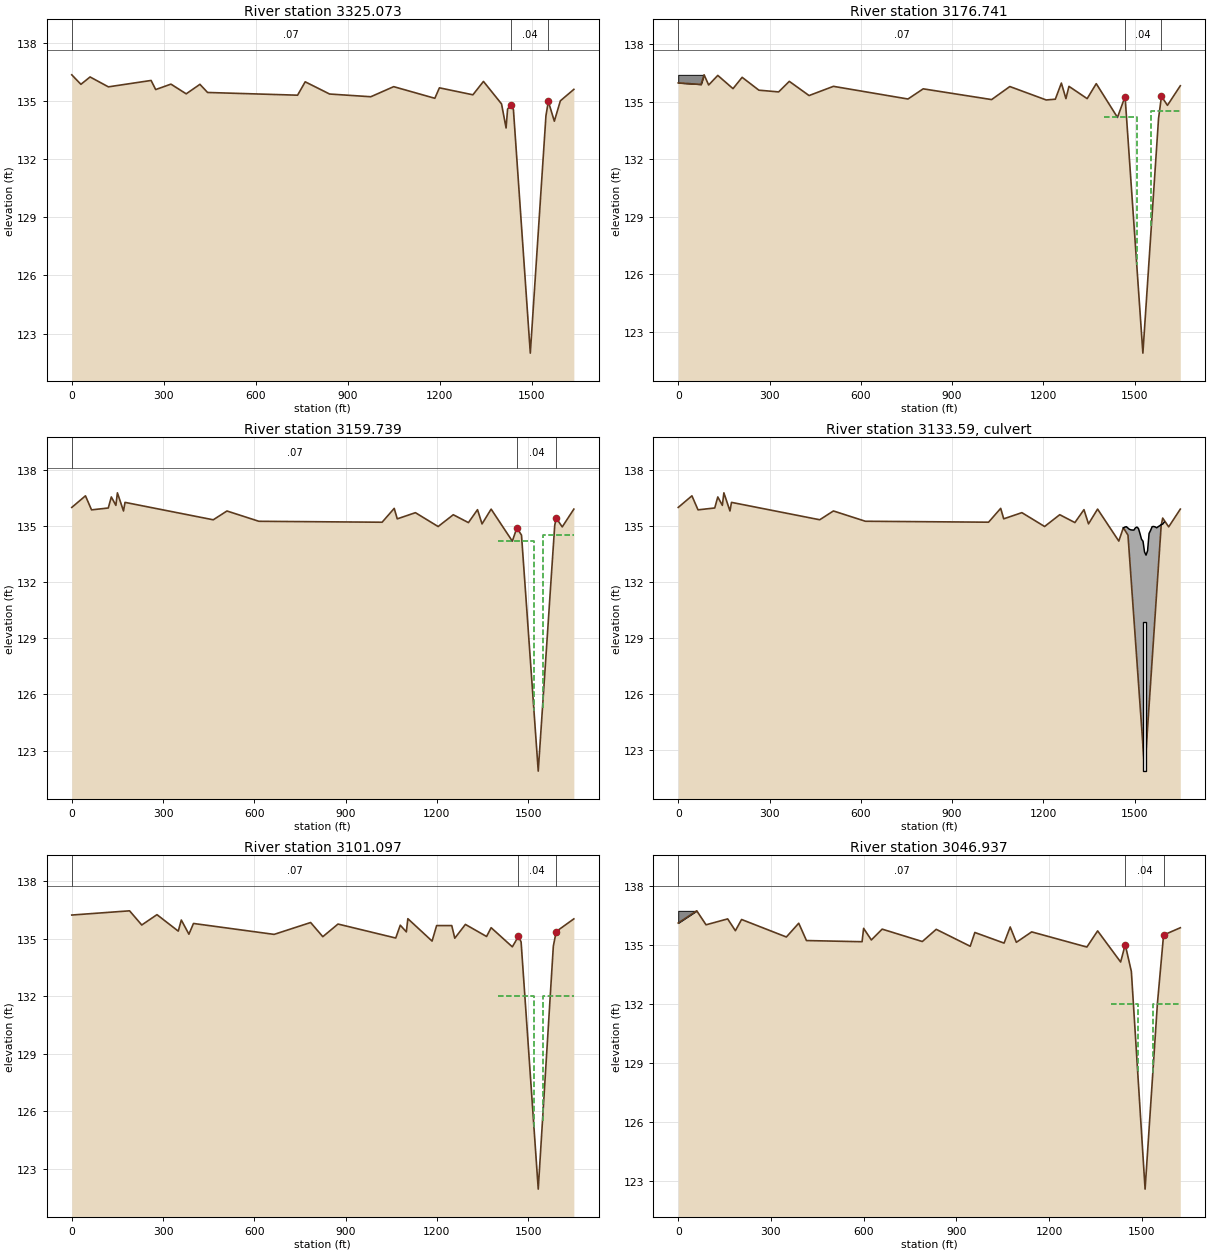
Type RM Length L Ch R = 1 ,3325.073,141.73,148.33,154.46
XS GIS Cut Line= 5
2995580.3305425213863130.2368358 2995814.003959713862157.9215232
2995833.7293139413861865.32958872995853.9084074513861566.0089931
2995856.8624697813861522.1911674
#Sta/Elev= 30
       0  136.34   29.85  135.85    59.7  136.23   119.4  135.72  258.71  136.05
  273.63  135.58  323.38  135.86  373.13  135.36  417.91  135.85  442.79  135.43
  736.32  135.29  761.19  135.98   840.8  135.35  975.12  135.21  1049.7  135.73
 1183.91  135.13 1198.82  135.67 1308.01  135.31 1342.44     136 1401.45  134.84
 1416.21   133.6 1421.12  134.57 1430.96  134.79 1440.14  134.55 1495.21  121.99
 1546.21  134.23 1553.91  134.97 1573.58  133.95 1593.26     135 1637.17  135.59
#Mann= 3 , 0 , 0
       0     .07       0 1430.96     .04       0 1553.91     .07       0
Bank Sta=1430.96,1553.91
XS Rating Curve= 0 ,0
Exp/Cntr=0.3,0.1

Type RM Length L Ch R = 1 ,3176.741,15.79,17,17.81
XS GIS Cut Line= 4
2995713.6954332713863170.54384182995898.2852871913862187.7282221
2996009.5987128613861595.05945992996018.2686430213861548.8974788
#Sta/Elev= 30
       0  135.98      75   135.9      85   136.4     100  135.87     130  136.37
     180  135.68     210  136.27     265   135.6     330  135.51     365  136.06
     430  135.32     510   135.8     755  135.14     805  135.67  1029.9  135.11
 1089.71  135.79 1209.32  135.09 1239.22  135.13 1259.15  135.97 1274.11  135.16
 1284.07   135.8 1343.88  135.16 1373.78  135.94 1443.55  134.18 1468.47  135.27
    1527   121.9  1578.5  134.13 1588.08  135.28 1607.73  134.81    1650  135.83
#Mann= 3 , 0 , 0
       0     .07       0 1468.47     .04       0 1588.08     .07       0
#XS Ineff= 2 ,-1
    1400    1507  134.18    1555    1650  134.52
Permanent Ineff=
       F       F
#Block Obstruct= 2 , 0
       0      85   136.4               0
Bank Sta=1468.47,1588.08
XS Rating Curve= 0 ,0
Exp/Cntr=0.5,0.3

Type RM Length L Ch R = 1 ,3159.739,58.85,58.64,58.63
BEGIN DESCRIPTION:
Upstream Section - HP&L EASEMENT #1
END DESCRIPTION:
Node Name=G
XS GIS Cut Line= 4
2995719.5940435213863174.42998882995904.1838974513862191.6143692
2996027.6469051113861597.24679152996036.3811396113861555.1993034
#Sta/Elev= 30
       0  135.98      45   136.6      65  135.85     120  135.95     130  136.54
     145  136.09     150  136.76     170  135.79     175  136.25     465  135.32
     510  135.79     615  135.24  1019.9  135.19 1059.71  135.93 1069.66  135.37
 1129.37   135.7 1204.01  134.96 1253.77  135.59 1303.53  135.17 1333.38  135.86
 1348.31   135.1 1378.17  135.89 1447.83  134.18 1462.76  134.89    1478   134.5
    1533   121.9 1587.15  135.02 1592.13  135.41 1611.83  134.94    1650  135.89
#Mann= 3 , 0 , 0
       0     .07       0 1462.76     .04       0 1592.13     .07       0
#XS Ineff= 2 ,-1
    1400    1519  134.18    1547    1650 134.525
Permanent Ineff=
       F       F
Bank Sta=1462.76,1592.13
XS Rating Curve= 0 ,0
Exp/Cntr=0.5,0.3

Type RM Length L Ch R = 2 ,3133.59 ,,,
BEGIN DESCRIPTION:
HP&L EASEMENT #1
END DESCRIPTION:
Node Name=HP&L EASMT #1
Bridge Culvert--1,0,-1,-1, 0
Deck Dist Width WeirC Skew NumUp NumDn MinLoCord MaxHiCord MaxSubmerge Is_Ogee
10.5,35,2.6,0, 28, 28, , , 0.98, 0, 0,0,,
 1462.76 1467.73 1472.71 1477.68 1482.66 1487.63 1492.61 1497.59 1502.56 1507.54
 1512.51 1517.49 1522.47 1527.44 1532.42 1537.39 1542.37 1547.34 1552.32  1557.3
 1562.27 1567.25 1572.22  1577.2 1582.18 1587.15 1592.13  1597.1
  134.88  134.93  134.95  134.88  134.81  134.78  134.77  134.77  134.89  134.93
  134.85  134.58  134.28  134.17   133.6  133.43  133.66  134.59  134.75  134.95
  134.96  134.94  134.89  134.95     135  135.06  135.09  135.19
                                                                                
                                                                                
                                                                
 1462.76 1467.73 1472.71 1477.68 1482.66 1487.63 1492.61 1497.59 1502.56 1507.54
 1512.51 1517.49 1522.47 1527.44 1532.42 1537.39 1542.37 1547.34 1552.32  1557.3
 1562.27 1567.25 1572.22  1577.2 1582.18 1587.15 1592.13  1597.1
  134.88  134.93  134.95  134.88  134.81  134.78  134.77  134.77  134.89  134.93
  134.85  134.58  134.28  134.17   133.6  133.43  133.66  134.59  134.75  134.95
  134.96  134.94  134.89  134.95     135  135.06  135.09  135.19
                                                                                
                                                                                
                                                                
BR Coef=-1 , 0 , 0 ,, 0 ,,,0.8,-1,,0,
WSPro=,,,, 1 ,,,, 0 ,,,, 0 ,,,,-1 ,-1 ,-1 , 0 , 0 , 0 , 0 , 0
Culvert=2,8,8,35,0.015,0.5,1,10,1,121.88,1533,121.93,1533,Culvert #1  , 0 ,10.5
Culvert Bottom n=0.015
BC Design=,, 0 ,, 0 ,,,,,,
BC Use User HTab Curves=0
BC User HTab FreeFlow(D)= 0

Type RM Length L Ch R = 1 ,3101.097,54.3,54.16,54.51
BEGIN DESCRIPTION:
Downstream Section - HP&L EASEMENT #1
END DESCRIPTION:
Node Name=F
XS GIS Cut Line= 4
2995861.7597696913863189.75148052995962.8356830313862194.8728929
2996086.2986906913861600.50531522996095.0329251913861558.4578271
#Sta/Elev= 30
       0  136.24     190  136.46     230  135.72     280  136.26     350   135.4
     360  135.98     385  135.24     400   135.8     665  135.23     785  135.85
     825  135.11     875  135.77 1064.69  135.04 1079.61  135.71 1099.52  135.36
 1104.49  136.05 1184.11  134.88 1199.03  135.69 1248.79  135.69 1258.74  135.03
 1293.58  135.75 1363.24  135.12 1378.17  135.58 1447.83  134.58 1467.73  135.12
 1476.66  134.84    1533  121.93 1582.62  134.62 1592.13  135.38    1650  136.04
#Mann= 3 , 0 , 0
       0     .07       0 1467.73     .04       0 1592.13     .07       0
#XS Ineff= 2 ,-1
    1400    1519     132    1547    1650     132
Permanent Ineff=
       F       F
Bank Sta=1467.73,1592.13
XS Rating Curve= 0 ,0
Exp/Cntr=0.5,0.3

Type RM Length L Ch R = 1 ,3046.937,523.55,511.65,503.06
XS GIS Cut Line= 4
2995915.3597281113863175.15538112996017.5242219413862180.3880137
2996140.4045536113861607.7201958 2996148.648959713861569.2977004
#Sta/Elev= 30
       0  136.12      60  136.74      90  136.03     160  136.33     185  135.73
     205   136.3     350  135.41     390  136.11     415  135.23     595  135.17
     600  135.85     625  135.26     660  135.81     790  135.18     835   135.8
     945  134.94     960  135.64  1054.6   135.1 1074.45  135.92 1094.31  135.14
 1143.94  135.67 1322.63   134.9 1357.38  135.72 1431.83  134.14 1446.72  135.02
 1466.58  133.66    1511   122.6 1550.96  132.04 1570.81  135.51    1625  135.88
#Mann= 3 , 0 , 0
       0     .07       0 1446.72     .04       0 1570.81     .07       0
#XS Ineff= 2 ,-1
    1400    1487     132    1536    1650     132
Permanent Ineff=
       F       F
#Block Obstruct= 2 , 0
       0      60  136.74               0
Bank Sta=1446.72,1570.81
XS Rating Curve= 0 ,0
Exp/Cntr=0.3,0.1

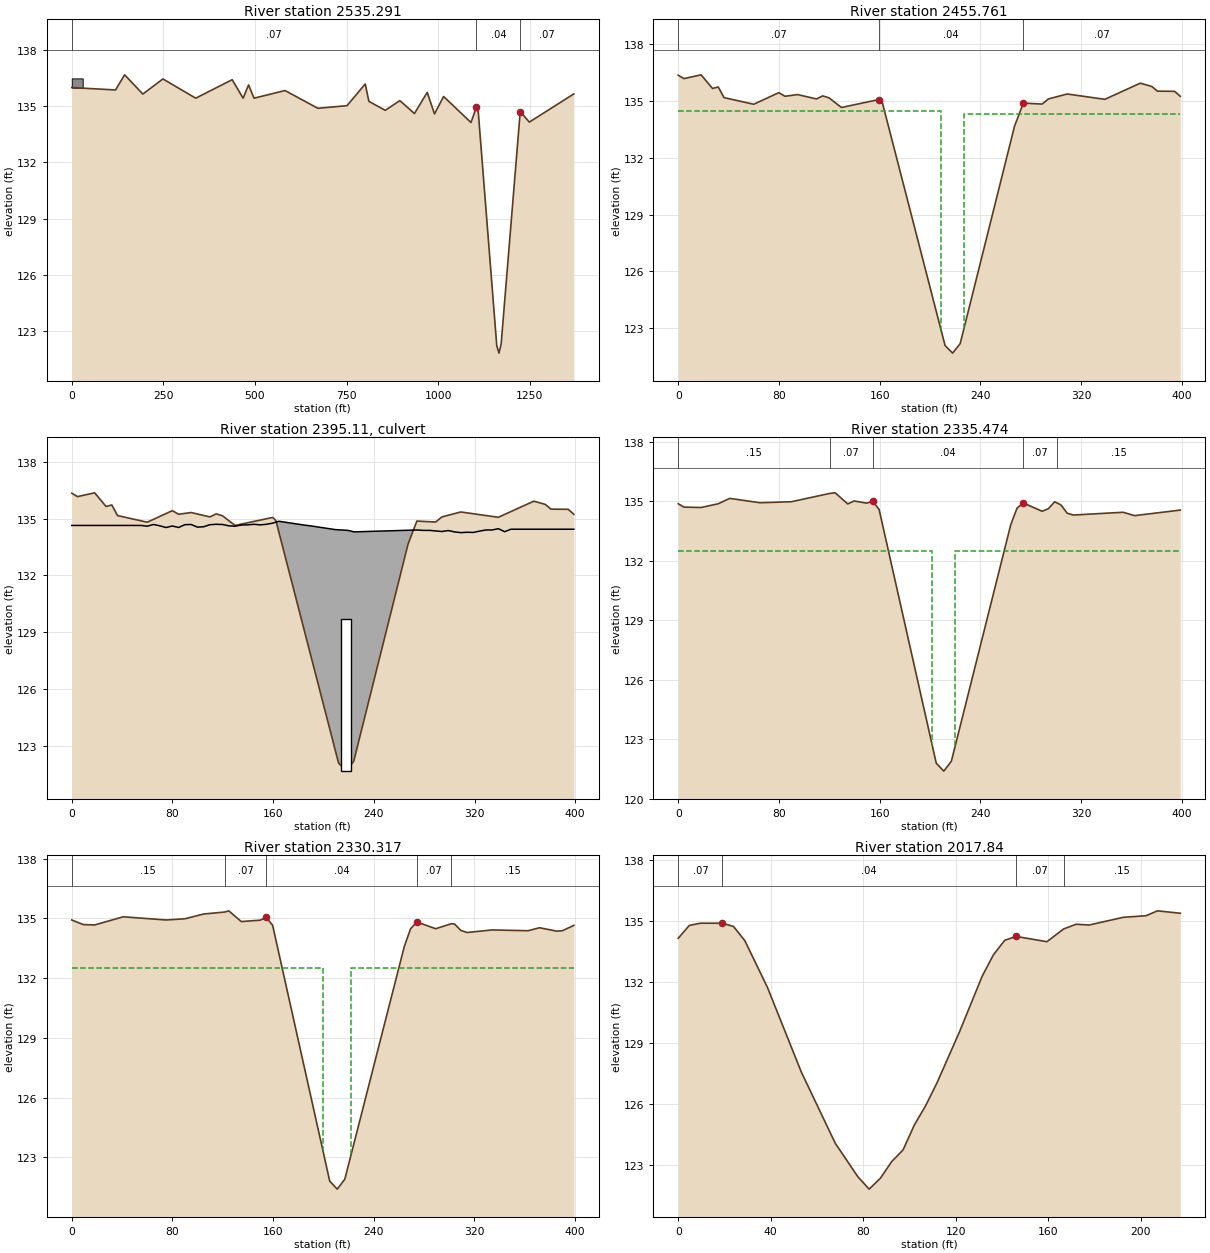
Type RM Length L Ch R = 1 ,2535.291,79.43,79.53,79.79
XS GIS Cut Line= 4
2996623.48888928 13863051.1119942996577.26325995 13862052.180921
2996586.8462460313861753.6405076 2996632.860261613861698.6849089
#Sta/Elev= 30
       0  136.01   119.4  135.88  144.28  136.69  194.03  135.66  248.76  136.47
  338.31  135.44  437.81  136.43  467.66  135.44  482.59  136.15  497.51  135.44
  582.09  135.85  671.64   134.9  751.24  135.04  800.99   136.2  810.94  135.27
  855.72  134.79  895.52  135.31  935.32  134.62  970.15  135.75  990.05   134.6
 1014.93  135.53 1089.61  134.14 1104.54  134.96 1109.52  134.69    1160   122.2
    1166   121.8    1172   122.3 1224.02  134.72 1248.91  134.16 1370.37  135.67
#Mann= 3 , 0 , 0
       0     .07       0 1104.54     .04       0 1224.02     .07       0
#XS Ineff= 2 ,-1
    1000 1104.54  134.64 1224.02 1298.89  134.48
Permanent Ineff=
       F       F
#Block Obstruct= 2 , 0
       0   29.85   136.5               0
Bank Sta=1104.54,1224.02
XS Rating Curve= 0 ,0
Exp/Cntr=0.5,0.3

Type RM Length L Ch R = 1 ,2455.761,120.16,120.29,120.15
BEGIN DESCRIPTION:
Upstream Section - ELROD RD
END DESCRIPTION:
Node Name=E
XS GIS Cut Line= 4
2996654.5508350313862107.92556022996656.2644142813862057.9548596
2996666.5081601913861759.23728122996668.2217394413861709.2665806
#Sta/Elev= 30
       0  136.34    4.55  136.16   18.18  136.36   27.27  135.64   31.82  135.72
   36.36  135.16   59.96  134.81   79.89  135.42   84.87  135.23   94.83  135.32
  109.78  135.09  114.76  135.25  119.74  135.15   129.7  134.64  159.59  135.06
  162.15   134.9     212   122.1     218   121.7     224   122.2  267.16  133.65
  274.17  134.87  289.11  134.82   294.1  135.09  309.04  135.35  338.93  135.07
  367.08  135.92  376.17  135.75  380.71   135.5  394.35  135.49  398.89  135.23
#Mann= 3 , 0 , 0
       0     .07       0  159.59     .04       0  274.17     .07       0
#XS Ineff= 2 ,-1
       0     209  134.43     227  398.89  134.31
Permanent Ineff=
       F       F
Bank Sta=159.59,274.17
XS Rating Curve= 0 ,0
Exp/Cntr=0.5,0.3

Type RM Length L Ch R = 2 ,2395.11 ,,,
BEGIN DESCRIPTION:
ELROD RD
END DESCRIPTION:
Node Name=ELROD RD
Bridge Culvert--1,0,-1,-1, 0
Deck Dist Width WeirC Skew NumUp NumDn MinLoCord MaxHiCord MaxSubmerge Is_Ogee
48.5,30,2.6,0, 63, 63, , , 0.98, 0, 2,2,,
       0      50   54.98   59.96   64.94   69.93   74.91   79.89   84.87   89.85
   94.83   99.82   104.8  109.78  114.76  119.74  124.72   129.7  134.69  139.67
  144.65  149.63  154.61  159.59  164.58  169.56  174.54  179.52   184.5  189.48
  194.47  199.45  204.43  209.41  214.39  219.37  224.35  229.34  234.32   239.3
  244.28  249.26  254.24  259.23  264.21  269.19  274.17  279.15  284.13  289.11
   294.1  299.08  304.06  309.04  314.02     319  323.99  328.97  333.95  338.93
  343.91  348.89  398.89
  134.64  134.64  134.64   134.6  134.69  134.62  134.53  134.61  134.53  134.68
  134.69  134.55  134.57  134.68   134.7  134.69  134.62   134.6  134.66  134.67
   134.7  134.67   134.7  134.76  134.86  134.81  134.76  134.71  134.66  134.62
  134.57  134.52  134.47  134.42   134.4  134.38   134.3  134.31  134.32  134.33
  134.34  134.35  134.36  134.37  134.38  134.39   134.4  134.38  134.38  134.35
  134.32  134.37   134.3  134.26  134.28  134.27  134.34   134.4   134.4  134.47
  134.31  134.44  134.44
                                                                                
                                                                                
                                                                                
                                                                                
                                                                                
                                                                                
                        
       0      50   54.98   59.96   64.94   69.93   74.91   79.89   84.87   89.85
   94.83   99.82   104.8  109.78  114.76  119.74  124.72   129.7  134.69  139.67
  144.65  149.63  154.61  159.59  164.58  169.56  174.54  179.52   184.5  189.48
  194.47  199.45  204.43  209.41  214.39  219.37  224.35  229.34  234.32   239.3
  244.28  249.26  254.24  259.23  264.21  269.19  274.17  279.15  284.13  289.11
   294.1  299.08  304.06  309.04  314.02     319  323.99  328.97  333.95  338.93
  343.91  348.89  398.89
  134.64  134.64  134.64   134.6  134.69  134.62  134.53  134.61  134.53  134.68
  134.69  134.55  134.57  134.68   134.7  134.69  134.62   134.6  134.66  134.67
   134.7  134.67   134.7  134.69  134.68  134.67  134.66  134.65  134.64  134.63
  134.62  134.61   134.6   134.6  134.54   134.5  134.49  134.48  134.47  134.46
  134.45  134.44  134.43  134.42  134.41   134.4   134.4  134.38  134.38  134.35
  134.32  134.37   134.3  134.26  134.28  134.27  134.34   134.4   134.4  134.47
  134.31  134.44  134.44
                                                                                
                                                                                
                                                                                
                                                                                
                                                                                
                                                                                
                        
BR Coef=-1 , 0 , 0 ,, 0 ,,,0.8,-1,,0,
WSPro=,,,, 1 ,,,, 0 ,,,, 0 ,,,,-1 ,-1 ,-1 , 0 , 0 , 0 , 0 , 0
Culvert=2,8,8,100,0.015,0.5,1,10,1,121.68,218,121.38,211,Culvert #1  , 0 ,10
Culvert Bottom n=0.015
BC Design=,, 0 ,, 0 ,,,,,,
BC Use User HTab Curves=0
BC User HTab FreeFlow(D)= 0

Type RM Length L Ch R = 1 ,2335.474,5.17,5.16,5.14
BEGIN DESCRIPTION:
Downstream Section - ELROD RD
END DESCRIPTION:
Node Name=D
XS GIS Cut Line= 4
2996774.7690985213862107.92556022996776.4826777713862057.9548596
 2996786.726423713861759.23728122996788.4400029513861709.2665806
#Sta/Elev= 30
       0  134.88    4.55  134.71   18.18  134.69   31.82  134.88   40.91  135.15
   64.94  134.93   89.85  134.98  120.36   135.4  124.72  135.43  134.69  134.87
  139.67  135.02  149.63  134.91  154.61     135  159.59  134.59     205   121.8
     211   121.4     217   121.9  264.21  133.83  269.19  134.66  274.17  134.92
  289.11   134.5   294.1  134.63  299.08  134.98  300.61  134.93  304.06  134.82
  309.04   134.4  314.02  134.31  353.44  134.45  362.53  134.28  398.89  134.56
#Mann= 5 ,-1 , 0
       0     .15       0  120.36     .07       0  154.61     .04       0
  274.17     .07       0  300.61     .15       0
#XS Ineff= 2 ,-1
       0     202   132.5     220  398.89   132.5
Permanent Ineff=
       F       F
Bank Sta=154.61,274.17
XS Rating Curve= 0 ,0
Exp/Cntr=0.5,0.3

Type RM Length L Ch R = 1 ,2330.317,328.29,312.48,297.39
XS GIS Cut Line= 4
2996779.9400199513862109.00265782996781.6421162813862059.0316291
2996791.8205736113861760.21989082996793.5226699413861710.2488621
#Sta/Elev= 30
       0  134.92    9.09  134.69   18.18  134.67   40.91  135.08   74.92  134.92
   89.86  134.98  104.81  135.22  121.64  135.32  124.75  135.38  134.71  134.84
  149.66  134.91  154.64  135.05  159.63  134.65     205   121.8     211   121.4
     217   121.9  264.27  133.59  269.26  134.48  274.24  134.82  289.19  134.48
  301.43  134.73  304.14  134.72  309.12   134.4   314.1  134.29  334.04  134.42
  362.62  134.38  371.71  134.53  385.35  134.36  389.89  134.38  398.99  134.65
#Mann= 5 ,-1 , 0
       0     .15       0  121.64     .07       0  154.64     .04       0
  274.24     .07       0  301.43     .15       0
#XS Ineff= 2 ,-1
       0     200   132.5     222  398.99   132.5
Permanent Ineff=
       F       F
Bank Sta=154.64,274.24
XS Rating Curve= 0 ,0
Exp/Cntr=0.3,0.1

Type RM Length L Ch R = 1 ,2017.84 ,475.26,491.23,502.25
XS GIS Cut Line= 2
2997119.1509556913861950.75691132997058.9634120313861742.2757009
#Sta/Elev= 30
       0  134.14    4.78  134.77    9.56  134.88   19.12  134.88    23.9  134.72
   28.79  134.02   38.56  131.72   53.21  127.55   67.86  124.05   77.63   122.4
   82.52  121.79    87.4  122.33   92.29  123.15   97.17  123.72  102.06  124.95
  106.94   125.9  111.83  127.02  121.59  129.54  131.36  132.27  136.25  133.33
  141.13  134.04  146.02  134.23  159.34  133.97  166.61   134.6     172  134.83
  177.54  134.79  192.34  135.17   202.2  135.25  207.13  135.49     217  135.37
#Mann= 4 ,-1 , 0
       0     .07       0   19.12     .04       0  146.02     .07       0
  166.61     .15       0
Bank Sta=19.12,146.02
XS Rating Curve= 0 ,0
Exp/Cntr=0.3,0.1

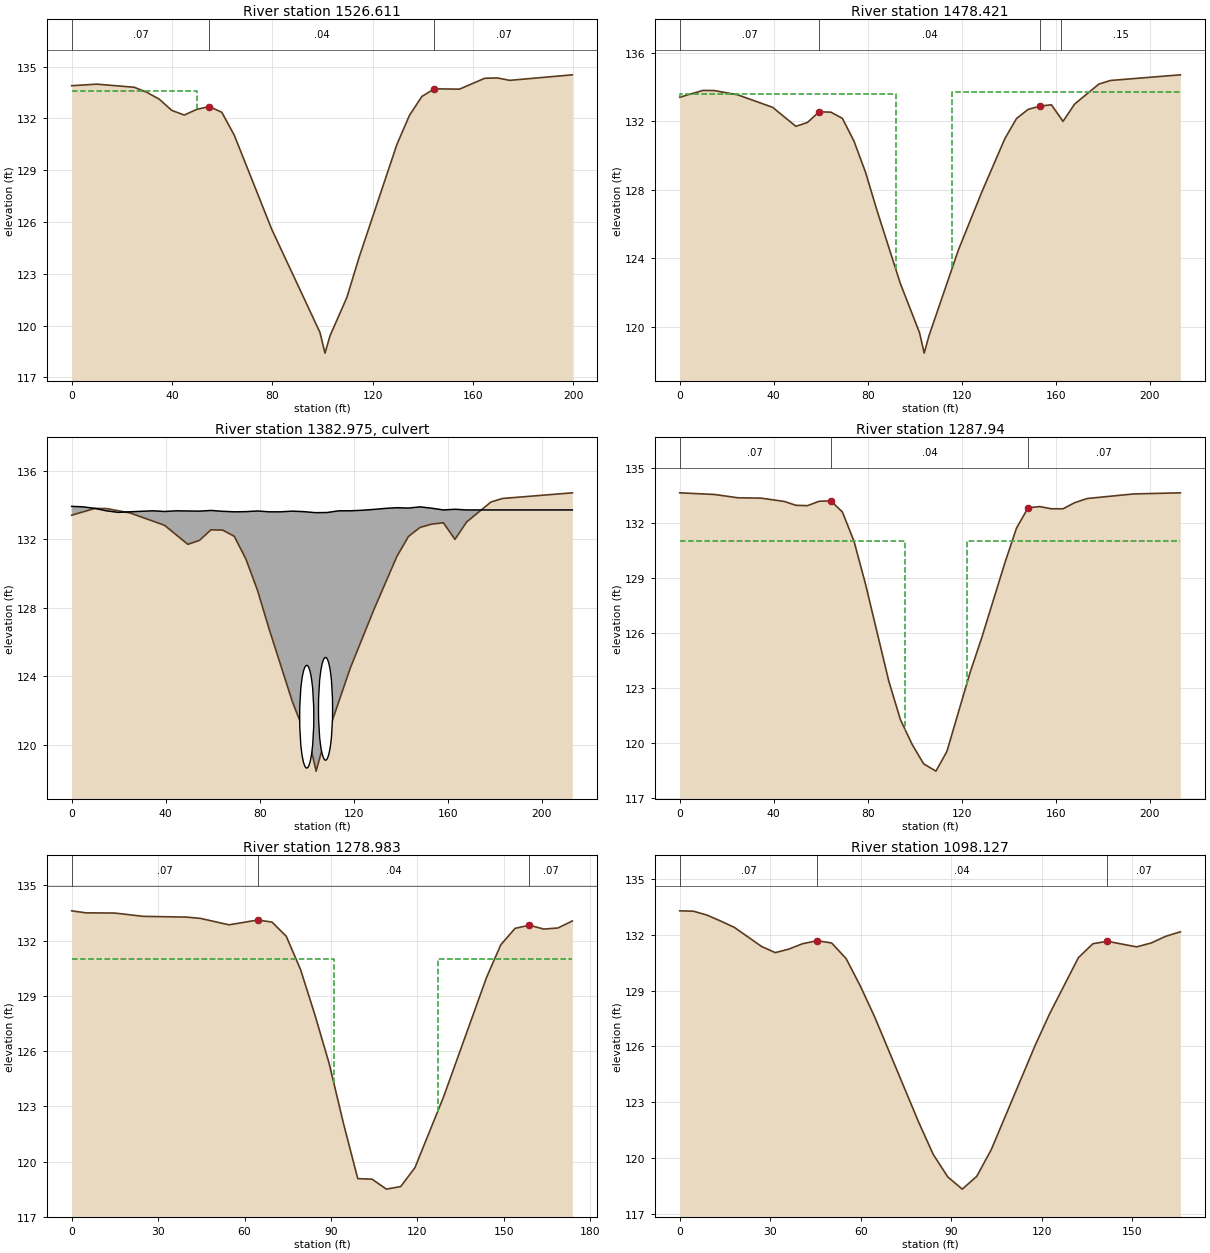
Type RM Length L Ch R = 1 ,1526.611,42.07,48.19,53.9
Node Name=C
XS GIS Cut Line= 2
2997549.2731269413861852.82338012997573.1477511113861654.6285665
#Sta/Elev= 26
       0  133.89    9.98  133.98   24.94   133.8   29.93  133.51   34.92  133.11
    39.9  132.46   44.89  132.19   49.88  132.52   54.87  132.68   59.86  132.35
   64.84  131.02   79.81  125.56      99   119.6     101   118.4     103   119.4
  109.74  121.63  114.72     124  129.69  130.49  134.68  132.17  139.66  133.27
  144.65  133.71  154.63  133.69  164.69  134.32  169.68  134.34  174.67   134.2
  199.63  134.52
#Mann= 3 ,-1 , 0
       0     .07       0   54.87     .04       0  144.65     .07       0
#XS Ineff= 1 ,-1
       0   49.88  133.58
Permanent Ineff=
       F
Bank Sta=54.87,144.65
XS Rating Curve= 0 ,0
Exp/Cntr=0.5,0.3

Type RM Length L Ch R = 1 ,1478.421,190.06,190.48,190
BEGIN DESCRIPTION:
Upstream Section - MASON RD
END DESCRIPTION:
XS GIS Cut Line= 2
2997579.8573833613861864.28956452997637.8044459413861659.3240952
#Sta/Elev= 30
       0   133.4    9.88   133.8   14.82  133.79   24.71  133.54   39.53  132.81
   49.41   131.7   54.35  131.93   59.29  132.55   64.24  132.53   69.18  132.17
   74.12  130.84   79.06  129.01      84  126.75   93.88  122.51     102  119.65
     104  118.45     106  119.45  118.59  124.49  128.47  127.85  138.35  130.99
  143.29  132.16  148.23  132.69  153.18  132.88  158.12  132.96  162.22  132.16
  163.06  131.99     168     133  178.33  134.17  183.28  134.38     213  134.71
#Mann= 4 ,-1 , 0
       0     .07       0   59.29     .04       0  153.18     .07       0
  162.22     .15       0
#XS Ineff= 2 ,-1
       0      92  133.58     116     213  133.71
Permanent Ineff=
       F       F
Bank Sta=59.29,153.18
XS Rating Curve= 0 ,0
Exp/Cntr=0.5,0.3

Type RM Length L Ch R = 2 ,1382.975,,,
BEGIN DESCRIPTION:
MASON RD
END DESCRIPTION:
Node Name=MASON RD
Bridge Culvert--1,0,-1,-1, 0
Deck Dist Width WeirC Skew NumUp NumDn MinLoCord MaxHiCord MaxSubmerge Is_Ogee
54,84,2.6,0, 36, 36, , , 0.98, 0, 0,0,,
       0    4.94    9.88   14.82   19.76   24.71   29.65   34.59   39.53   44.47
   49.41   54.35   59.29   64.24   69.18   74.12   79.06      84   88.94   93.88
   98.82  103.76  108.71  113.65  118.59  123.53  128.47  133.41  138.35  143.29
  148.23  153.18  158.12  163.06     168     213
  133.92  133.89   133.8  133.66  133.57   133.6  133.63  133.66  133.62  133.66
  133.65  133.64  133.68  133.63   133.6  133.61  133.65   133.6   133.6  133.64
  133.61  133.55  133.56  133.66  133.66  133.69  133.74   133.8  133.84  133.82
  133.89  133.81  133.71  133.75  133.71  133.71
                                                                                
                                                                                
                                                                                
                                                
       0    4.94    9.88   14.82   19.76   24.71   29.65   34.59   39.53   44.47
   49.41   54.35   59.29   64.24   69.18   74.12   79.06      84   88.94   93.88
   98.82  103.76  108.71  113.65  118.59  123.53  128.47  133.41  138.35  143.29
  148.23  153.18  158.12  163.06     168     213
  133.92  133.89   133.8  133.66  133.57   133.6  133.63  133.66  133.62  133.66
  133.65  133.64  133.68  133.63   133.6  133.61  133.65   133.6   133.6  133.64
  133.61  133.55  133.56  133.66  133.66  133.69  133.74   133.8  133.84  133.82
  133.89  133.81  133.71  133.75  133.71  133.71
                                                                                
                                                                                
                                                                                
                                                
BR Coef=-1 , 0 , 0 ,, 0 ,,,0.8,-1,,0,
WSPro=,,,, 1 ,,,, 0 ,,,, 0 ,,,,-1 ,-1 ,-1 , 0 , 0 , 0 , 0 , 0
Culvert=1,6,,145,0.013,0.5,1,1,1,118.63,100,118.36,105,Culvert #1  , 0 ,27
Culvert Bottom n=0.013
Culvert=1,6,,145,0.013,0.5,1,1,1,119.09,108,118.45,113,Culvert #2  , 0 ,27
Culvert Bottom n=0.013
BC Design=,, 0 ,, 0 ,,,,,,
BC Use User HTab Curves=0
BC User HTab FreeFlow(D)= 0

Type RM Length L Ch R = 1 ,1287.94 ,9.92,8.96,7.9
BEGIN DESCRIPTION:
Downstream Section - MASON RD
END DESCRIPTION:
XS GIS Cut Line= 2
 2997762.691007213861915.97974992997820.6380697813861711.0142805
#Sta/Elev= 30
       0  133.63   14.82  133.54   24.71  133.36   34.59  133.34   44.47  133.16
   49.41  132.95   54.35  132.93   59.29  133.17   64.24  133.19   69.18  132.59
   74.12     131   79.06  128.64   88.94  123.36   93.88  121.26   98.82  119.92
  103.76  118.85     109  118.45  113.65  119.52  123.53  123.83  128.47  125.72
  138.35  129.82  143.29  131.71  148.23  132.82  153.18  132.88  158.12  132.76
  163.06  132.76     168  133.09  173.37  133.32  193.19  133.57     213  133.63
#Mann= 3 ,-1 , 0
       0     .07       0   64.24     .04       0  148.23     .07       0
#XS Ineff= 2 ,-1
       0      96     131     122     213     131
Permanent Ineff=
       F       F
Bank Sta=64.24,148.23
XS Rating Curve= 0 ,0
Exp/Cntr=0.5,0.3

Type RM Length L Ch R = 1 ,1278.983,191.54,180.86,169.95
Node Name=B
XS GIS Cut Line= 2
2997773.0453171913861923.48793692997815.6466099513861754.9968041
#Sta/Elev= 27
       0  133.62    4.97  133.51    14.9   133.5   24.83  133.32   39.72  133.28
   44.69  133.21   54.62  132.86   64.55  133.12   69.52  133.01   74.48  132.24
   79.45  130.43   84.41  127.98   89.38  125.33   94.34  122.08   99.31  119.08
  104.28  119.05  109.24  118.51  114.21  118.65  119.17  119.68   129.1  123.52
     144     130  148.97  131.78  153.93  132.67   158.9  132.84  163.86  132.63
  168.83  132.69  173.79  133.07
#Mann= 3 ,-1 , 0
       0     .07       0   64.55     .04       0   158.9     .07       0
#XS Ineff= 2 ,-1
       0      91     131     127  173.79     131
Permanent Ineff=
       F       F
Bank Sta=64.55,158.9
XS Rating Curve= 0 ,0
Exp/Cntr=0.3,0.1

Type RM Length L Ch R = 1 ,1098.127,221.76,207.6,195.09
XS GIS Cut Line= 4
2997982.4559876213861935.32091852997980.1010054513861894.6956717
2997974.2552166113861793.85499412997972.8569254413861769.7329951
#Sta/Elev= 29
       0   133.3    4.52  133.28    9.04  133.07   13.56  132.75   18.09  132.41
   27.13  131.38   31.65  131.05   36.17  131.24   40.69  131.53    45.5  131.69
   50.31  131.57   55.12  130.73   59.93  129.22   64.74  127.53   79.17  121.92
   83.98  120.19   88.79  118.98    93.6  118.32   98.41  119.01  103.22  120.45
  117.65  126.02  122.46  127.73  132.08  130.78  136.89  131.53   141.7  131.66
  151.37  131.36   156.2  131.57  161.03  131.93  165.87  132.17
#Mann= 3 ,-1 , 0
       0     .07       0    45.5     .04       0   141.7     .07       0
Bank Sta=45.5,141.7
XS Rating Curve= 0 ,0
Exp/Cntr=0.3,0.1

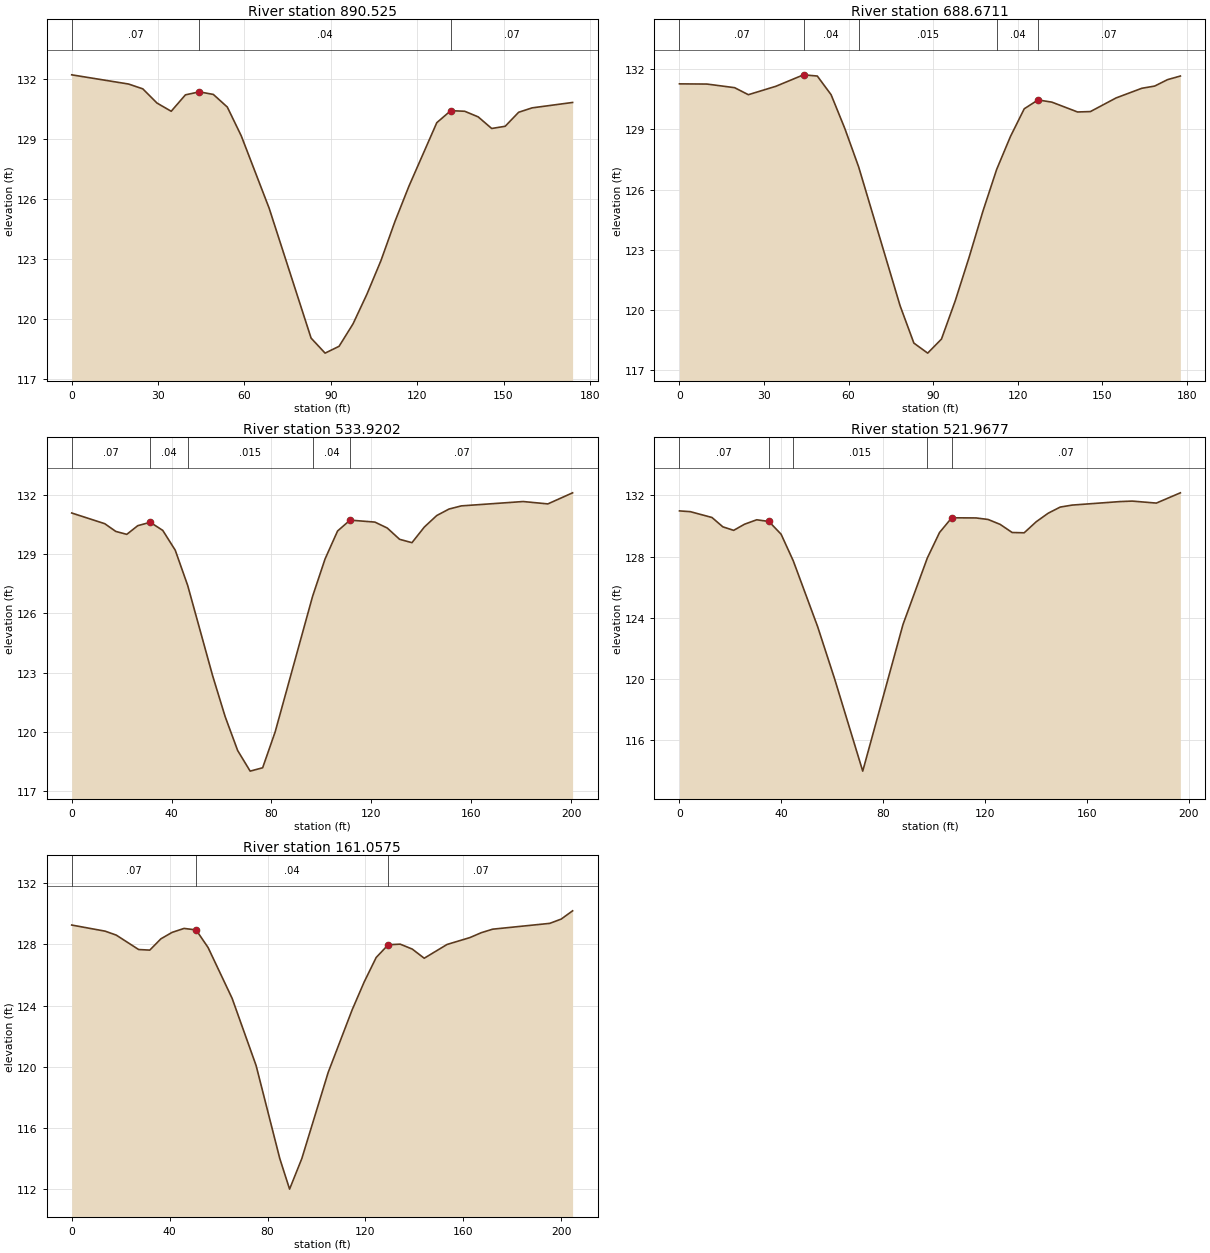
Type RM Length L Ch R = 1 ,890.525 ,205.09,201.85,198.83
XS GIS Cut Line= 4
2998216.8623429413861889.36333332998200.6113911913861853.3607806
2998160.7000536913861764.94100992998145.2863706113861730.7934404
#Sta/Elev= 28
       0  132.21   19.75  131.75   24.69  131.51   29.63   130.8   34.56  130.39
    39.5  131.21   44.35  131.36    49.2  131.23   54.05   130.6    58.9  129.16
    68.6  125.54   83.15  119.06   88.01  118.31   92.86  118.65   97.71  119.77
  102.56  121.26  107.41  122.93  112.26  124.88  117.11  126.64  126.81  129.82
  131.66  130.42  136.51  130.39  141.19  130.11  145.88  129.53  150.56  129.64
  155.24  130.34  159.93  130.56  173.98  130.83
#Mann= 3 ,-1 , 0
       0     .07       0   44.35     .04       0  131.66     .07       0
Bank Sta=44.35,131.66
XS Rating Curve= 0 ,0
Exp/Cntr=0.3,0.1

Type RM Length L Ch R = 1 ,688.6711,119.13,154.75,193.35
XS GIS Cut Line= 4
2998403.6743052813861794.45112152998384.4085957713861760.4151004
2998338.5871651213861679.46381872998316.1252677713861639.7808272
#Sta/Elev= 29
       0  131.27    9.78  131.26   19.56  131.08   24.44  130.73   34.22  131.15
   44.01  131.72    48.9  131.66    53.8  130.73   58.69  129.04   63.59  127.13
   78.28  120.22   83.17  118.36   88.07  117.86   92.96  118.56   97.86  120.47
  102.76  122.63  107.65  124.92  112.55  127.01  117.44  128.65  122.34  130.03
  127.23  130.47  132.13  130.36  141.25  129.87  145.81  129.89  154.93  130.57
  164.05  131.05  168.61  131.16  173.17  131.48  177.73  131.66
#Mann= 5 ,-1 , 0
       0     .07       0   44.01     .04       0   63.59    .015       0
  112.55     .04       0  127.23     .07       0
Bank Sta=44.01,127.23
XS Rating Curve= 0 ,0
Exp/Cntr=0.3,0.1

Type RM Length L Ch R = 1 ,533.9202,10.68,11.95,12.89
XS GIS Cut Line= 4
2998461.5091633613861804.34020942998476.4586085213861782.5079039
2998527.30660394 13861708.2485382998574.8261939413861638.8500548
#Sta/Elev= 30
       0  131.07   13.23  130.53   17.64  130.14   22.05  129.99   26.46  130.43
   31.46   130.6   36.46  130.19   41.46  129.19   46.46   127.4   56.46  122.83
   61.46  120.77   66.46  119.06   71.46  118.02   76.46  118.19   81.46     120
   96.46  126.86  101.46  128.75  106.46  130.16  111.46  130.71  121.41  130.61
  126.36  130.31   131.3  129.74  136.25  129.57   141.2  130.36  146.15  130.94
  151.09  131.27  156.04  131.43  180.78  131.65  190.67  131.53  200.57  132.09
#Mann= 5 ,-1 , 0
       0     .07       0   31.46     .04       0   46.46    .015       0
   96.46     .04       0  111.46     .07       0
Bank Sta=31.46,111.46
XS Rating Curve= 0 ,0
Exp/Cntr=0.3,0.1

Type RM Length L Ch R = 1 ,521.9677,360.18,360.91,359.93
XS GIS Cut Line= 4
2998470.0609835213861808.27392852998485.2312287813861787.7162268
2998539.2642571913861714.49458852998586.91770519 13861649.917946
#Sta/Elev= 30
       0  130.99    4.26  130.94   12.77  130.56   17.03  129.95   21.29  129.72
   25.55  130.12   30.34  130.41   35.13   130.3   39.92  129.47   44.71  127.73
   54.29  123.43      61     120      72     114   87.81  123.57   97.39  127.92
  102.18  129.58  106.97  130.54  116.55  130.53  121.27  130.43  125.99  130.11
  130.71  129.58  135.43  129.56  140.15  130.28  144.87  130.84   149.6  131.24
  154.32  131.37   173.2   131.6  177.92  131.63  187.36   131.5   196.8  132.17
#Mann= 5 ,-1 , 0
       0     .07       0   35.13     .04       0   44.71    .015       0
   97.39     .04       0  106.97     .07       0
Bank Sta=35.13,106.97
XS Rating Curve= 0 ,0
Exp/Cntr=0.3,0.1

Type RM Length L Ch R = 1 ,161.0575,,,
Node Name=A
XS GIS Cut Line= 4
2998730.3291637713862057.41942762998755.14571519 13862024.783338
2998817.4900786913861942.79432882998854.1747166113861894.5503308
#Sta/Elev= 30
       0  129.27   13.67  128.87   18.22  128.61   27.33  127.67   31.89  127.63
   36.44  128.37      41  128.79    45.9  129.05   50.81  128.95   55.71   127.8
   65.52  124.48   75.33  120.08      85     114      89     112      94     114
  104.76  119.63  114.57  123.73  119.48  125.55  124.38  127.15  129.29  127.98
  134.19  128.02   139.1   127.7     144   127.1  153.32     128  162.65  128.45
  167.31  128.77  171.97     129  195.28  129.38  199.95  129.66  204.61   130.2
#Mann= 3 ,-1 , 0
       0     .07       0   50.81     .04       0  129.29     .07       0
Bank Sta=50.81,129.29
XS Rating Curve= 0 ,0
Exp/Cntr=0.3,0.1

Chan Stop Cuts=-1
Use User Specified Reach Order=0
Composite Channel Slope=5